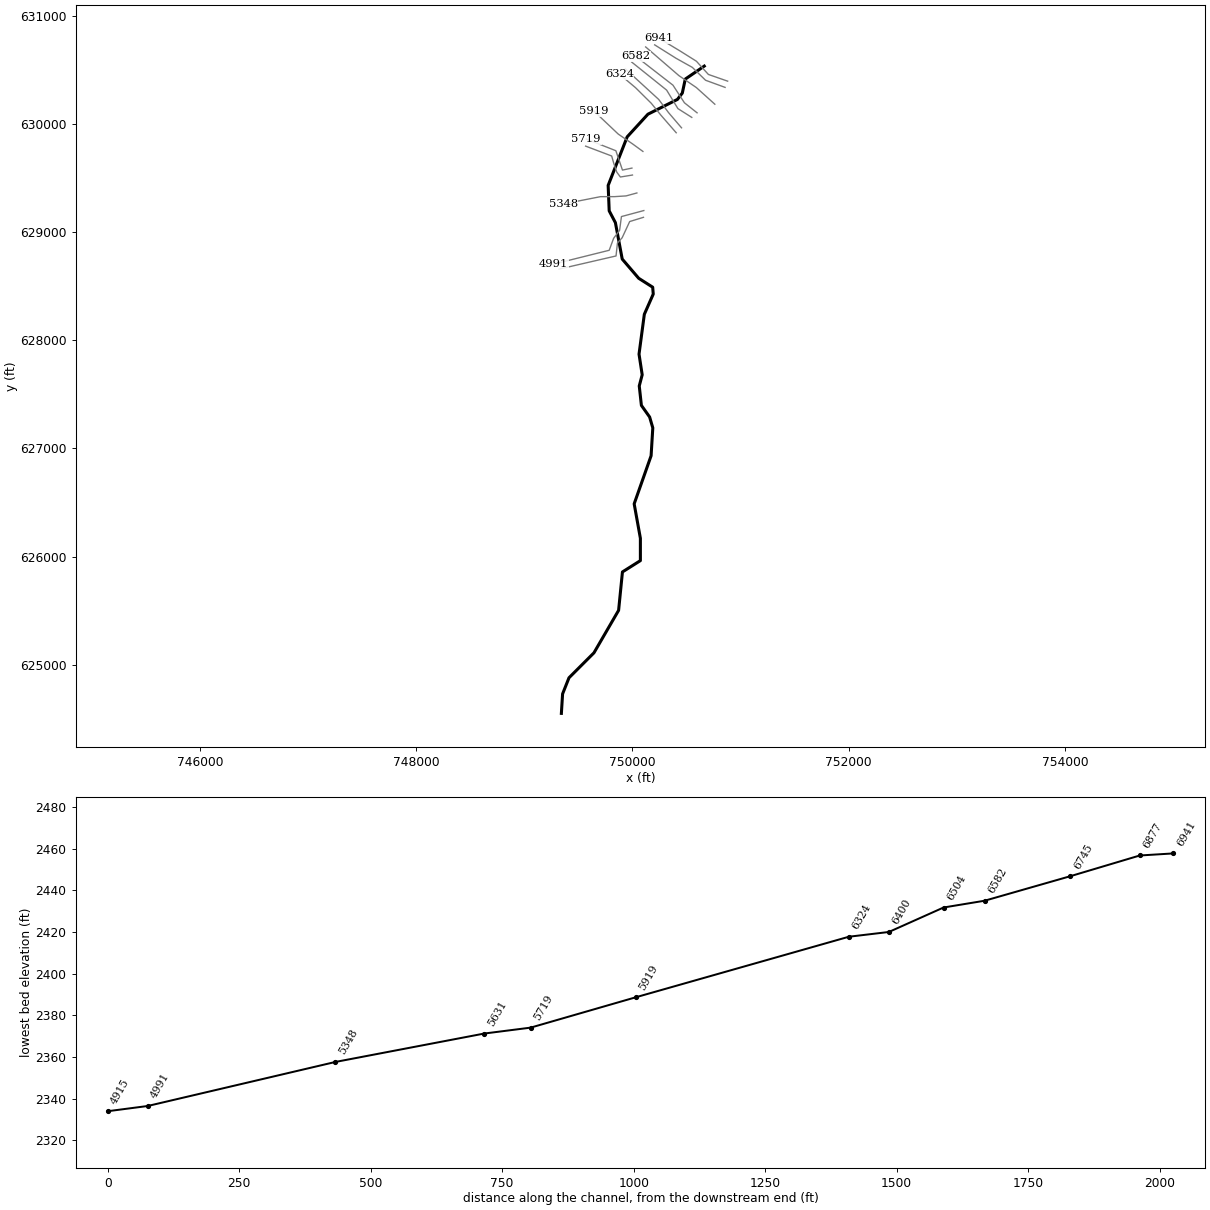
--- lds_fisher_crk.prj (project) ---

Proj Title=Fisher Creek Limited Detail Study
Current Plan=p02
Default Exp/Contr=0.3,0.1
English Units
Geom File=g01
Flow File=f02
Plan File=p02
Y Axis Title=Elevation
X Axis Title(PF)=Main Channel Distance
X Axis Title(XS)=Station
BEGIN DESCRIPTION:
Fisher Creek
END DESCRIPTION:
DSS Export Rating Curves= 0
DSS Export Rating Curve Sorted= 0
DSS Export Volume Flow Curves= 0
DXF OffsetX= 0
DXF OffsetY= 0
DXF ScaleX= 1
DXF ScaleY= 10

--- lds_fisher_crk.p02 (plan) ---

Plan Title=Floodway Run
Program Version=3.13
Short Identifier=Multiple
Geom File=g01
Flow File=f02
Subcritical Flow
K Sum by GR= 0
Std Step Tol= 0.01
Critical Tol= 0.01
Num of Std Step Trials= 20
Max Error Tol= 0.3
Flow Tol Ratio= 0.001
Split Flow NTrial= 30
Split Flow Tol= 0.02
Split Flow Ratio= 0.02
Log Output Level= 0
Friction Slope Method= 1
Unsteady Friction Slope Method= 2
Unsteady Bridges Friction Slope Method= 1
Parabolic Critical Depth
Global Vel Dist= 0 , 0 , 0
Global Log Level= 0
CheckData=True
Encroach Param=-1 ,7,7, 2
Encroach River=Fisher Creek
Encroach Reach=Reach-1
Encroach Node=6941
       1 4973.18    5030
Encroach Node=6877
       1 4980.39  5023.6
Encroach Node=6745
       1  4948.5    5016
Encroach Node=6582
       1 4971.58  5088.3
Encroach Node=6504
       1 4981.54    5072
Encroach Node=6400
       1  4989.6    5040
Encroach Node=6324
       1 4981.53    5036
Encroach Node=5919
       1    4980    5017
Encroach Node=5719
       4      .7
Encroach Node=5631
       4      .7
Encroach Node=5348
       1    4950    5024
Encroach Node=4991
       1 3498.75    3573
Encroach Node=4915
       1 3496.97 3564.81
Encroach Node=4595
       4      .7
Encroach Node=4349
       1 4986.13    5038
Encroach Node=4136
       1 4931.88    5050
Encroach Node=4066
       1 4938.32  5038.5
Encroach Node=4047
       1  4945.5    5042
Encroach Node=4006
       1 4965.86 5030.17
Encroach Node=3831
       1    4954 5020.88
Encroach Node=3597
       1    4904    5032
Encroach Node=3533
       1    4965    5025
Encroach Node=3445
       1    4890    5034
Encroach Node=3363
       1    4903    5020
Encroach Node=3328
       1  4913.7  5042.2
Encroach Node=3265
       1  4938.6  5040.1
Encroach Node=3058
       1    4985    5040
Encroach Node=2982
       1  4912.7 5031.66
Encroach Node=2684
       1    4922  5012.6
Encroach Node=2297
       1 4822.56  5012.1
Encroach Node=2215
       1 4884.57 5067.51
Encroach Node=1992
       1    4952    5011
Encroach Node=1703
       1 4982.25    5065
Encroach Node=1515
       1    4963  5019.5
Encroach Node=1222
       1    4983    5075
Encroach Node=1166
       1    4983    5077
Encroach Node=831
       1    4975    5055
Encroach Node=530
       1    4960    5035
Encroach Node=189
       1    4973    5018
Encroach Node=133
       1    4978    5017
Encroach Node=18
       4      .7
BEGIN DESCRIPTION:
Multiple Run
END DESCRIPTION:
Computation Interval=1HOUR
Output Interval=1HOUR
Run HTab= 0
Run UNet= 0
Run PostProcess= 0
UNET Theta= 1
UNET Theta Warmup= 1
UNET ZTol= 0.02
UNET ZSATol= 0.05
UNET MxIter= 20
UNET MaxInSteps= 0
UNET DtIC= 0
UNET DtMin= 0
UNET MaxCRTS= 20
UNET WFStab= 2
UNET SFStab= 1
UNET WFX= 1
UNET SFX= 1
UNET DSS MLevel= 4
UNET DZMax Abort= 100
UNET Convert EG Bridges=-1
UNET Use Existing IB Tables=-1
UNET Froude Reduction=False
UNET Froude Limit= 1
UNET Froude Power= 10
Instantaneous Interval=1HOUR
Write IC File= 0
Echo Input=False
Echo Output=False
Write Detailed= 0
Detailed Automatic Start=False, 10

--- lds_fisher_crk.f02 (steady flow) ---

Flow Title=Floodway
Program Version=3.13
Number of Profiles= 2
Profile Names=100-year,100-FW
River Rch & RM=Fisher Creek,Reach-1         ,6941
    1200    1200
River Rch & RM=Fisher Creek,Reach-1         ,6582
    1220    1220
River Rch & RM=Fisher Creek,Reach-1         ,5719
    1720    1720
River Rch & RM=Fisher Creek,Reach-1         ,4136
    1810    1810
Boundary for River Rch & Prof#=Fisher Creek,Reach-1         , 1
Up Type= 0
Dn Type= 3
Dn Slope=0.033
Boundary for River Rch & Prof#=Fisher Creek,Reach-1         , 2
Up Type= 0
Dn Type= 3
Dn Slope=0.033
DSS Import GetInterval= 0
DSS Import GetPeak= 0
DSS Import FillOption= 0

--- lds_fisher_crk.g01 (geometry) ---

Geom Title=Existing Conditions
Program Version=3.13

River Reach=Fisher Creek    ,Reach-1
Reach XY= 30
       750665.45       630535.76       750489.86       630415.65
       750462.34       630286.15       750417.26       630227.64
       750144.48       630090.96        749952.6       629881.54
        749776.6       629432.43       749786.18       629197.07
       749843.57         629088.       749906.72       628751.24
       750058.96       628573.64       750188.42       628491.16
       750193.64       628427.47       750111.16       628240.59
       750062.09       627872.05       750091.32       627680.99
       750064.18       627577.64       750084.02       627398.06
       750160.23       627290.53       750189.46        627190.3
        750173.8       626932.43        750017.2       626487.67
       750074.63       626169.25       750074.63       625962.53
       749908.76       625857.95       749873.24       625502.75
       749645.33       625110.06       749414.45       624879.19
       749355.25        624730.2         749344.       624550.02

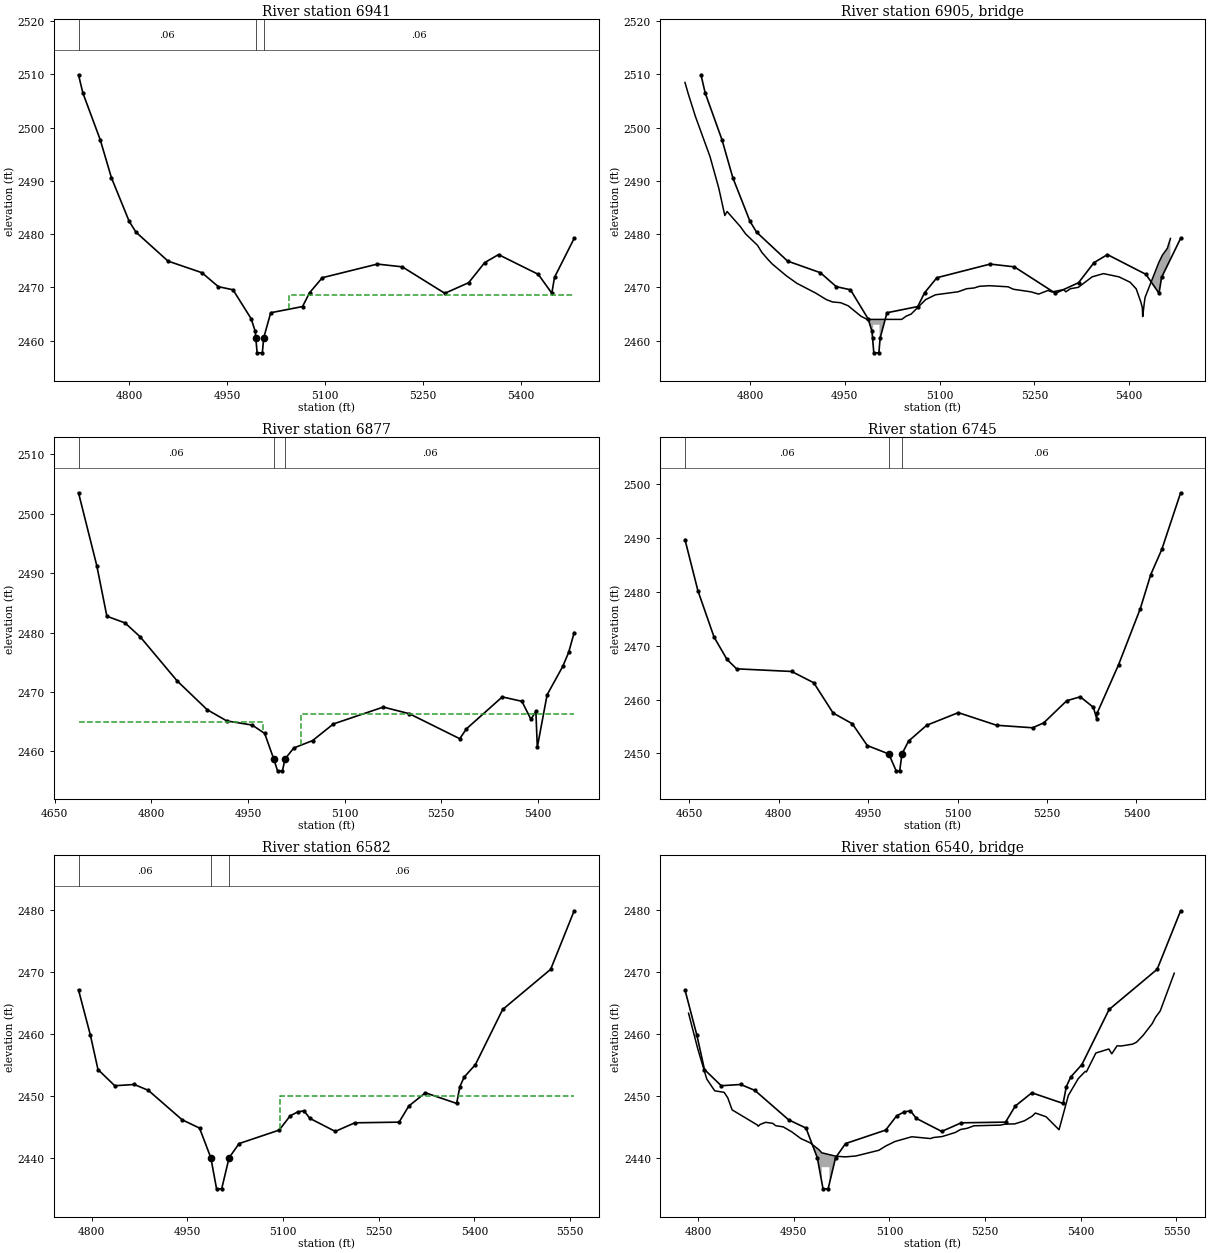
Type RM Length L Ch R = 1 ,6941    ,64,64,64
BEGIN DESCRIPTION:
XS 56
END DESCRIPTION:
XS GIS Cut Line= 5
       750881.66       630396.49       750703.43       630458.66
       750592.68       630580.81       750439.58       630676.91
        750247.4       630792.54
#Sta/Elev= 30
  4722.6 2509.94  4729.2 2506.55  4755.8 2497.75    4773  2490.6  4800.1 2482.43
  4810.5 2480.39  4859.6 2474.95  4911.5 2472.77  4936.6 2470.15  4959.1 2469.56
  4986.9 2464.12  4993.1 2461.75    4994  2460.5    4996 2457.72    5004 2457.72
    5006  2460.5  5016.8 2465.25  5065.5 2466.41  5076.2 2468.99  5095.8 2471.83
    5180 2474.39  5218.2 2473.87  5283.3  2468.9  5319.8 2470.89  5344.3 2474.66
  5365.5 2476.17  5426.4 2472.46  5447.1 2468.91  5451.2  2471.9  5481.3 2479.22
#Mann= 3 ,-1 , 0
  4722.6     .06       0    4994     .05       0    5006     .06       0
#XS Ineff= 2 , 0
       0    4965 2465.64    5045       0  2468.5
Permanent Ineff=
       F       F
Bank Sta=4994,5006
Exp/Cntr=0.5,0.3

Type RM Length L Ch R = 3 ,6905    ,,,
BEGIN DESCRIPTION:
XS 55 TOR
Structure ID: XS 55
Approximate Survey Structure
END DESCRIPTION:
Bridge Culvert--1,0,-1,-1, 0
Deck Dist Width WeirC Skew NumUp NumDn MinLoCord MaxHiCord MaxSubmerge Is_Ogee
30,12,3,0, 60, 60, , , , 0, 1,1,,
  4697.3  4702.6  4713.9    4737  4750.8  4760.3  4763.9  4784.8  4793.2    4812
    4819  4828.4  4835.3  4857.5  4874.4  4903.8  4920.9  4930.8  4943.4  4955.4
    4976  4985.5    4995    4995    5005    5005  5040.1  5047.1  5055.1  5077.9
  5093.4  5129.4  5142.8  5154.5  5163.2  5179.1  5208.4  5216.8  5244.8  5256.6
  5271.4  5277.6  5296.1  5299.8  5306.9  5319.4  5341.3  5359.3    5384  5401.5
    5411  5418.4  5420.7  5421.3  5423.8  5425.1  5446.9  5452.6  5460.2  5465.2
  2508.5 2506.31 2502.08 2494.54 2488.63 2483.51 2484.26 2481.44 2480.06 2477.91
 2476.57 2475.28 2474.41  2472.2 2470.77 2468.96 2467.72 2467.27 2467.14 2466.56
 2464.57    2464    2464    2464    2464    2464    2464  2464.6 2465.01 2467.71
 2468.62 2469.19 2469.76  2469.9 2470.22 2470.33 2470.12 2469.66 2469.17 2468.75
 2469.43 2469.15  2469.6 2469.18 2469.76 2470.02 2471.99  2472.6 2471.98 2470.97
 2469.74 2467.25 2466.21 2464.52 2467.08 2468.15 2474.72  2476.1 2477.33  2479.2
 2437.72 2437.72 2437.72 2437.72 2437.72 2437.72 2437.72 2437.72 2437.72 2437.72
 2437.72 2437.72 2437.72 2437.72 2437.72 2437.72 2437.72 2437.72 2437.72 2437.72
 2437.72 2437.72 2437.72    2463    2463 2437.72 2437.72 2437.72 2437.72 2437.72
 2437.72 2437.72 2437.72 2437.72 2437.72 2437.72 2437.72 2437.72 2437.72 2437.72
 2437.72 2437.72 2437.72 2437.72 2437.72 2437.72 2437.72 2437.72 2437.72 2437.72
 2437.72 2437.72 2437.72 2437.72 2437.72 2437.72 2437.72 2437.72 2437.72 2437.72
  4697.3  4702.6  4713.9    4737  4750.8  4760.3  4763.9  4784.8  4793.2    4812
    4819  4828.4  4835.3  4857.5  4874.4  4903.8  4920.9  4930.8  4943.4  4955.4
    4976  4985.5    4995    4995    5005    5005  5040.1  5047.1  5055.1  5077.9
  5093.4  5129.4  5142.8  5154.5  5163.2  5179.1  5208.4  5216.8  5244.8  5256.6
  5271.4  5277.6  5296.1  5299.8  5306.9  5319.4  5341.3  5359.3    5384  5401.5
    5411  5418.4  5420.7  5421.3  5423.8  5425.1  5446.9  5452.6  5460.2  5465.2
  2508.5 2506.31 2502.08 2494.54 2488.63 2483.51 2484.26 2481.44 2480.06 2477.91
 2476.57 2475.28 2474.41  2472.2 2470.77 2468.96 2467.72 2467.27 2467.14 2466.56
 2464.57    2464    2464    2464    2464    2464    2464  2464.6 2465.01 2467.71
 2468.62 2469.19 2469.76  2469.9 2470.22 2470.33 2470.12 2469.66 2469.17 2468.75
 2469.43 2469.15  2469.6 2469.18 2469.76 2470.02 2471.99  2472.6 2471.98 2470.97
 2469.74 2467.25 2466.21 2464.52 2467.08 2468.15 2474.72  2476.1 2477.33  2479.2
 2437.72 2437.72 2437.72 2437.72 2437.72 2437.72 2437.72 2437.72 2437.72 2437.72
 2437.72 2437.72 2437.72 2437.72 2437.72 2437.72 2437.72 2437.72 2437.72 2437.72
 2437.72 2437.72 2437.72    2463    2463 2437.72 2437.72 2437.72 2437.72 2437.72
 2437.72 2437.72 2437.72 2437.72 2437.72 2437.72 2437.72 2437.72 2437.72 2437.72
 2437.72 2437.72 2437.72 2437.72 2437.72 2437.72 2437.72 2437.72 2437.72 2437.72
 2437.72 2437.72 2437.72 2437.72 2437.72 2437.72 2437.72 2437.72 2437.72 2437.72
BR Coef= 1 , 1 , 0 ,1.25, 0 ,,,0.8,0,2,0,
WSPro=,,,, 1 ,,,, 0 ,,,, 0 ,,,,-1 ,-1 ,-1 , 0 , 0 , 0 , 0 , 0
BC Design=,, 0 ,, 0 ,,,,,,
BC HTab HWMax=2509.94

Type RM Length L Ch R = 1 ,6877    ,132,132,132
BEGIN DESCRIPTION:
XS 54
END DESCRIPTION:
XS GIS Cut Line= 5
       750857.97       630338.95       750677.37       630404.91
       750555.22       630523.81       750403.75        630608.5
       750206.68       630732.28
#Sta/Elev= 30
  4687.2 2503.55  4715.5  2491.3  4731.2 2482.76  4759.4 2481.63  4782.9 2479.29
  4840.2 2471.87  4886.9 2467.01  4917.4 2465.12  4956.7 2464.43    4976 2463.02
  4990.1 2458.72    4996 2456.72  5003.6 2456.72  5007.6 2458.72  5021.2 2460.57
  5050.3 2461.81  5082.7 2464.62  5160.1 2467.46  5200.5 2466.34  5278.7 2462.13
  5289.1  2463.8  5344.7 2469.17  5375.1 2468.43  5389.1  2465.4  5396.8 2466.74
    5399 2460.69  5414.2 2469.52  5438.6 2474.33  5447.7 2476.69  5456.2    2480
#Mann= 3 ,-1 , 0
  4687.2     .06       0  4990.1     .05       0  5007.6     .06       0
#XS Ineff= 2 , 0
       0    4973  2464.9    5032       0 2466.36
Permanent Ineff=
       F       F
Bank Sta=4990.1,5007.6
Exp/Cntr=0.5,0.3

Type RM Length L Ch R = 1 ,6745    ,163,163,163
BEGIN DESCRIPTION:
XS 53
END DESCRIPTION:
XS GIS Cut Line= 4
        750763.2       630183.26       750592.27       630337.26
        750431.5       630447.26       750123.49       630712.96
#Sta/Elev= 30
  4642.7 2489.69  4664.4  2480.2  4691.5  2471.6  4713.2 2467.45  4729.3 2465.71
  4821.7 2465.22  4858.8 2463.12  4891.2 2457.51  4923.4 2455.52  4948.6 2451.47
  4984.7 2449.91    4997 2446.78    5003 2446.78  5006.7 2449.91  5017.9 2452.31
  5048.3 2455.24  5101.3 2457.58  5165.5 2455.24    5226 2454.77  5244.6 2455.68
  5283.3  2459.8  5305.9 2460.52  5327.9 2458.57  5333.5 2456.46  5334.2 2457.49
  5370.1 2466.45  5406.7  2476.9  5424.2 2483.21  5442.7 2487.87  5474.3 2498.38
#Mann= 3 ,-1 , 0
  4642.7     .06       0  4984.7     .05       0  5006.7     .06       0
Bank Sta=4984.7,5006.7
Exp/Cntr=0.5,0.3

Type RM Length L Ch R = 1 ,6582    ,78,78,78
BEGIN DESCRIPTION:
XS 52
END DESCRIPTION:
XS GIS Cut Line= 4
       750599.04       630103.72       750481.93       630196.44
       750376.06       630359.31        750033.8       630624.96
#Sta/Elev= 30
  4779.6 2467.12  4798.3 2459.78  4810.1 2454.27  4836.4 2451.65    4867 2451.85
  4889.1  2450.9    4942 2446.15  4969.3 2444.81    4987 2440.02    4996    2435
    5004    2435  5015.6 2440.02  5031.3 2442.31  5094.2 2444.49  5111.3 2446.78
  5123.2 2447.42    5133  2447.6  5142.2 2446.38    5182 2444.27  5212.6 2445.66
  5282.1 2445.77  5297.2 2448.36  5323.3 2450.51  5372.3 2448.79  5377.3  2451.5
  5384.2 2453.06  5401.7 2455.06  5444.4 2463.96  5519.7 2470.45  5556.5  2479.9
#Mann= 3 ,-1 , 0
  4779.6     .06       0    4987     .05       0  5015.6     .06       0
#XS Ineff= 3 ,-1
  4779.6  4957.5    2443  5042.5 5095.16 2440.26    5096  5556.5    2450
Permanent Ineff=
       F       F       F
Bank Sta=4987,5015.6
Exp/Cntr=0.5,0.3

Type RM Length L Ch R = 3 ,6540    ,,,
BEGIN DESCRIPTION:
XS 51 TOR
Structure ID: XS 51
Approximate Survey Structure
END DESCRIPTION:
Bridge Culvert--1,0,-1,-1, 0
Deck Dist Width WeirC Skew NumUp NumDn MinLoCord MaxHiCord MaxSubmerge Is_Ogee
36.5,11,3,0, 60, 60, , , , 0, 1,1,,
  4785.2  4799.7  4813.7  4826.2    4841  4846.7  4853.5  4892.7  4894.3  4897.3
  4905.9  4917.1  4921.9  4933.5  4947.2  4961.3  4975.5  4989.5    4994    4994
    5006    5006  5016.2  5030.6  5047.2  5083.6  5094.7  5108.9  5135.1  5164.4
  5169.2  5182.6  5203.3  5211.8  5221.7  5232.5  5274.3  5281.3  5296.6  5311.7
  5323.6  5328.8  5345.6  5365.9  5380.5    5396  5406.9  5408.8  5423.6  5443.9
  5448.6  5456.8  5463.7  5481.2  5487.5  5497.6  5512.1  5517.3  5524.5  5546.5
 2463.36 2457.58 2452.74 2450.83 2450.58 2449.69 2447.75 2445.33 2445.11 2445.39
 2445.74 2445.58 2445.19 2445.01 2444.19 2443.11 2442.45 2441.33 2440.82 2440.82
 2440.52 2440.52 2440.27 2440.16  2440.3 2441.23 2441.94 2442.65 2443.41 2443.12
 2443.29 2443.44  2444.1 2444.59 2444.77 2445.18 2445.29 2445.45 2445.49 2445.99
 2446.72 2447.24 2446.64 2444.54 2450.08 2452.79 2453.96 2453.88 2456.93 2457.58
  2456.8 2458.09 2458.07 2458.37 2458.69 2459.77  2461.7 2462.72 2463.72 2469.82
    2412    2412    2412    2412    2412    2412    2412    2412    2412    2412
    2412    2412    2412    2412    2412    2412    2412    2412    2412  2438.5
  2438.5    2412    2412    2412    2412    2412    2412    2412    2412    2412
    2412    2412    2412    2412    2412    2412    2412    2412    2412    2412
    2412    2412    2412    2412    2412    2412    2412    2412    2412    2412
    2412    2412    2412    2412    2412    2412    2412    2412    2412    2412
  4785.2  4799.7  4813.7  4826.2    4841  4846.7  4853.5  4892.7  4894.3  4897.3
  4905.9  4917.1  4921.9  4933.5  4947.2  4961.3  4975.5  4989.5    4994    4994
    5006    5006  5016.2  5030.6  5047.2  5083.6  5094.7  5108.9  5135.1  5164.4
  5169.2  5182.6  5203.3  5211.8  5221.7  5232.5  5274.3  5281.3  5296.6  5311.7
  5323.6  5328.8  5345.6  5365.9  5380.5    5396  5406.9  5408.8  5423.6  5443.9
  5448.6  5456.8  5463.7  5481.2  5487.5  5497.6  5512.1  5517.3  5524.5  5546.5
 2463.36 2457.58 2452.74 2450.83 2450.58 2449.69 2447.75 2445.33 2445.11 2445.39
 2445.74 2445.58 2445.19 2445.01 2444.19 2443.11 2442.45 2441.33 2440.82 2440.82
 2440.52 2440.52 2440.27 2440.16  2440.3 2441.23 2441.94 2442.65 2443.41 2443.12
 2443.29 2443.44  2444.1 2444.59 2444.77 2445.18 2445.29 2445.45 2445.49 2445.99
 2446.72 2447.24 2446.64 2444.54 2450.08 2452.79 2453.96 2453.88 2456.93 2457.58
  2456.8 2458.09 2458.07 2458.37 2458.69 2459.77  2461.7 2462.72 2463.72 2469.82
    2412    2412    2412    2412    2412    2412    2412    2412    2412    2412
    2412    2412    2412    2412    2412    2412    2412    2412    2412  2438.5
  2438.5    2412    2412    2412    2412    2412    2412    2412    2412    2412
    2412    2412    2412    2412    2412    2412    2412    2412    2412    2412
    2412    2412    2412    2412    2412    2412    2412    2412    2412    2412
    2412    2412    2412    2412    2412    2412    2412    2412    2412    2412
Abutment Skew #Up #Dn= , 2 , 2
    4994    4995
    2437    2433
    4994    4995
  2438.5 2432.75
Abutment Skew #Up #Dn= , 2 , 2
    5005    5006
    2433    2437
    5005    5006
 2432.75  2438.5
BR Coef= 1 , 1 , 0 ,1.25, 0 ,,,0.8,0,2,0,
WSPro=,,,, 1 ,,,, 0 ,,,, 0 ,,,,-1 ,-1 ,-1 , 0 , 0 , 0 , 0 , 0
BC Design=,, 0 ,, 0 ,,,,,,
BC HTab HWMax=2479.9

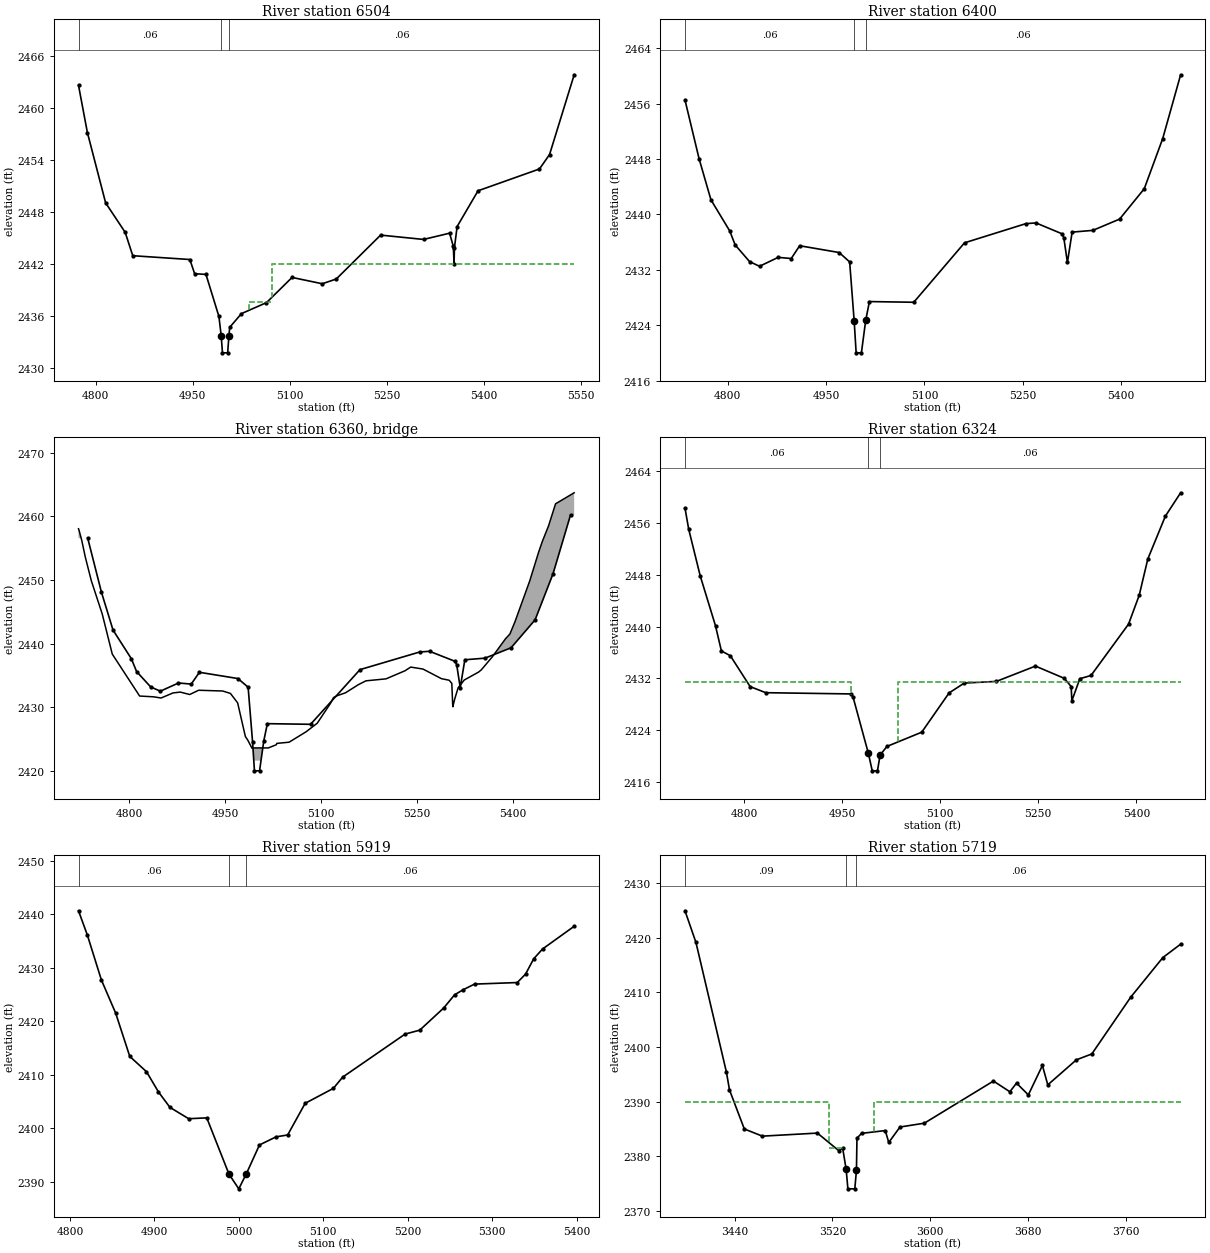
Type RM Length L Ch R = 1 ,6504    ,104,104,104
BEGIN DESCRIPTION:
XS 50
END DESCRIPTION:
XS GIS Cut Line= 4
       750549.96       630061.41       750421.67       630142.69
       750317.43       630313.71       749994.88        630572.5
#Sta/Elev= 30
  4773.6 2462.65  4787.3  2457.2  4815.5 2449.07  4845.7 2445.67  4857.4 2442.97
  4945.6 2442.53    4953 2440.89  4970.5 2440.81  4990.5 2435.95    4994 2433.75
    4996 2431.75    5004 2431.75    5006 2433.75  5007.2  2434.7  5025.3 2436.28
    5064 2437.55  5103.5 2440.46  5150.2 2439.73  5171.8 2440.28  5240.3 2445.35
  5306.6 2444.85  5346.8 2445.57  5352.6 2444.06  5353.8 2442.03  5354.3 2443.88
  5358.5 2446.34  5390.8 2450.47  5485.7 2452.99  5501.3 2454.66  5539.3 2463.87
#Mann= 3 ,-1 , 0
  4773.6     .06       0    4994     .05       0    5006     .06       0
#XS Ineff= 3 ,-1
  4773.6  4963.5          5036.5  5071.5 2437.66    5072  5539.3    2442
Permanent Ineff=
       F       F       F
Bank Sta=4994,5006
Exp/Cntr=0.5,0.3

Type RM Length L Ch R = 1 ,6400    ,76,76,76
BEGIN DESCRIPTION:
XS 49
END DESCRIPTION:
XS GIS Cut Line= 4
       750455.19       629964.95       750335.35       630105.23
       750244.14       630227.38       749935.64       630509.88
#Sta/Elev= 30
  4735.2 2456.55  4756.7 2448.05  4774.8 2442.11  4803.4 2437.62  4811.7 2435.59
  4833.7 2433.18  4848.8 2432.51  4877.2  2433.8  4897.1 2433.63  4909.9 2435.48
  4970.1  2434.5  4986.1 2433.14    4993  2424.6    4996    2420    5004    2420
  5010.6 2424.71  5016.2 2427.41  5083.8 2427.31  5161.1  2435.9  5254.5 2438.67
  5269.9 2438.78  5310.1 2437.19  5312.4 2436.63  5317.9 2433.06  5325.1 2437.45
  5356.6  2437.7  5397.4 2439.33    5435 2443.72  5463.1 2450.97  5490.4 2460.19
#Mann= 3 ,-1 , 0
  4735.2     .06       0    4993     .05       0  5010.6     .06       0
#XS Ineff= 2 , 0
       0    4960 2431.96    5040       0 2424.38
Permanent Ineff=
       F       F
Bank Sta=4993,5010.6
Exp/Cntr=0.5,0.3

Type RM Length L Ch R = 3 ,6360    ,,,
BEGIN DESCRIPTION:
XS 48 TOR
Structure ID: XS 48
Approximate Survey Structure
END DESCRIPTION:
Bridge Culvert--1,0,-1,-1, 0
Deck Dist Width WeirC Skew NumUp NumDn MinLoCord MaxHiCord MaxSubmerge Is_Ogee
35,10,3,0, 60, 60, , , , 0, 1,1,,
  4720.8  4721.6  4725.8  4731.4  4740.8  4757.9  4773.6  4816.4  4838.2  4849.9
  4868.7    4880  4894.7  4908.7  4946.4  4958.4  4969.7  4981.8  4985.6  4992.1
    4995    4995    5005    5005  5017.7  5030.2    5031  5050.2    5077  5094.2
    5115  5119.7  5125.3  5138.4  5158.6  5170.4  5201.8  5231.5  5240.4  5259.6
  5288.5  5300.6  5304.7    5306  5306.3  5309.4  5314.6  5324.2  5346.7  5350.8
    5368  5388.8  5395.6  5403.5  5426.6  5440.5  5446.3  5455.9    5467  5496.1
 2458.03 2457.81 2456.23 2453.59 2449.87 2444.64 2438.34 2431.75 2431.63 2431.44
 2432.24 2432.37 2431.99 2432.66 2432.54 2432.16 2430.68 2425.39 2424.82 2423.56
  2423.6  2423.6  2423.6  2423.6  2423.6  2424.1 2424.31  2424.5 2426.15 2427.48
 2430.61 2431.51  2431.8 2432.26 2433.54 2434.14 2434.45 2435.72  2436.3 2435.99
 2434.48 2434.23 2433.74  2430.6 2430.07 2431.33 2433.05 2434.27 2435.52 2435.86
  2437.9 2440.76  2441.5 2443.42 2449.84 2454.35 2456.04 2458.45 2461.95 2463.68
  2398.3  2398.3  2398.3  2398.3  2398.3  2398.3  2398.3  2398.3  2398.3  2398.3
  2398.3  2398.3  2398.3  2398.3  2398.3  2398.3  2398.3  2398.3  2398.3  2398.3
  2398.3  2421.6  2421.6  2398.3  2398.3  2398.3  2398.3  2398.3  2398.3  2398.3
  2398.3  2398.3  2398.3  2398.3  2398.3  2398.3  2398.3  2398.3  2398.3  2398.3
  2398.3  2398.3  2398.3  2398.3  2398.3  2398.3  2398.3  2398.3  2398.3  2398.3
  2398.3  2398.3  2398.3  2398.3  2398.3  2398.3  2398.3  2398.3  2398.3  2398.3
  4720.8  4721.6  4725.8  4731.4  4740.8  4757.9  4773.6  4816.4  4838.2  4849.9
  4868.7    4880  4894.7  4908.7  4946.4  4958.4  4969.7  4981.8  4985.6  4992.1
    4995    4995    5005    5005  5017.7  5030.2    5031  5050.2    5077  5094.2
    5115  5119.7  5125.3  5138.4  5158.6  5170.4  5201.8  5231.5  5240.4  5259.6
  5288.5  5300.6  5304.7    5306  5306.3  5309.4  5314.6  5324.2  5346.7  5350.8
    5368  5388.8  5395.6  5403.5  5426.6  5440.5  5446.3  5455.9    5467  5496.1
 2458.03 2457.81 2456.23 2453.59 2449.87 2444.64 2438.34 2431.75 2431.63 2431.44
 2432.24 2432.37 2431.99 2432.66 2432.54 2432.16 2430.68 2425.39 2424.82 2423.56
  2423.6  2423.6  2423.6  2423.6  2423.6  2424.1 2424.31  2424.5 2426.15 2427.48
 2430.61 2431.51  2431.8 2432.26 2433.54 2434.14 2434.45 2435.72  2436.3 2435.99
 2434.48 2434.23 2433.74  2430.6 2430.07 2431.33 2433.05 2434.27 2435.52 2435.86
  2437.9 2440.76  2441.5 2443.42 2449.84 2454.35 2456.04 2458.45 2461.95 2463.68
  2398.3  2398.3  2398.3  2398.3  2398.3  2398.3  2398.3  2398.3  2398.3  2398.3
  2398.3  2398.3  2398.3  2398.3  2398.3  2398.3  2398.3  2398.3  2398.3  2398.3
  2398.3  2421.6  2421.6  2398.3  2398.3  2398.3  2398.3  2398.3  2398.3  2398.3
  2398.3  2398.3  2398.3  2398.3  2398.3  2398.3  2398.3  2398.3  2398.3  2398.3
  2398.3  2398.3  2398.3  2398.3  2398.3  2398.3  2398.3  2398.3  2398.3  2398.3
  2398.3  2398.3  2398.3  2398.3  2398.3  2398.3  2398.3  2398.3  2398.3  2398.3
Abutment Skew #Up #Dn= , 2 , 2
    4995    4996
    2421    2415
    4995    4996
    2421 2417.72
Abutment Skew #Up #Dn= , 2 , 2
    5004    5005
    2415    2421
    5004    5005
 2417.72    2421
BR Coef= 1 , 1 , 0 ,1.25, 0 ,,,0.8,0,2,0,
WSPro=,,,, 1 ,,,, 0 ,,,, 0 ,,,,-1 ,-1 ,-1 , 0 , 0 , 0 , 0 , 0
BC Design=,, 0 ,, 0 ,,,,,,
BC HTab HWMax=2460.19

Type RM Length L Ch R = 1 ,6324    ,405,405,405
BEGIN DESCRIPTION:
XS 47
END DESCRIPTION:
XS GIS Cut Line= 5
       750406.11       629919.26       750265.31        630080.8
       750175.73       630191.55       750030.41       630335.57
        749879.8        630462.5
#Sta/Elev= 30
  4709.5 2458.32  4715.2 2455.04  4732.8 2447.84  4756.2 2440.12  4765.2 2436.24
  4778.9  2435.5  4809.2 2430.73  4833.1 2429.79  4962.8  2429.6  4966.5 2429.17
  4990.1 2420.41    4996 2417.72    5004 2417.72    5008 2420.16  5018.5 2421.49
  5071.7 2423.69  5113.6 2429.76  5136.9 2431.28  5185.8 2431.53  5245.7  2433.9
  5289.8 2432.01  5300.3 2430.74  5301.4 2428.55  5313.6 2431.95  5330.7 2432.45
  5388.1 2440.38  5404.4 2444.83  5417.6 2450.45  5444.5 2457.07  5467.8 2460.67
#Mann= 3 ,-1 , 0
  4709.5     .06       0  4990.1     .05       0    5008     .06       0
#XS Ineff= 2 , 0
       0    4964 2431.45    5036       0 2431.45
Permanent Ineff=
       F       F
Bank Sta=4990.1,5008
Exp/Cntr=0.5,0.3

Type RM Length L Ch R = 1 ,5919    ,200,200,200
BEGIN DESCRIPTION:
XS 46
END DESCRIPTION:
XS GIS Cut Line= 4
       750098.11       629746.64       750005.03       629814.33
       749869.64       629907.41       749646.25       630118.95
#Sta/Elev= 30
  4810.1 2440.69  4820.6 2436.13  4837.2 2427.74  4854.1 2421.54  4870.8 2413.44
  4890.6 2410.58  4904.8 2406.79  4918.4  2403.9  4940.6 2401.78    4962 2401.94
  4988.3 2391.41  4999.9 2388.66  5008.9 2391.49  5024.4 2396.87  5044.1 2398.39
  5057.8 2398.74  5078.5 2404.66  5111.9 2407.46    5123 2409.57  5196.9 2417.62
  5214.2 2418.35  5242.6  2422.5  5255.5 2424.97  5265.7 2425.92  5279.1 2426.97
  5329.7 2427.26  5339.5 2428.83  5349.2 2431.71  5359.6 2433.53  5397.1 2437.79
#Mann= 3 ,-1 , 0
  4810.1     .06       0  4988.3     .05       0  5008.9     .06       0
Bank Sta=4988.3,5008.9
Exp/Cntr=0.5,0.3

Type RM Length L Ch R = 1 ,5719    ,88,88,88
BEGIN DESCRIPTION:
XS 45
END DESCRIPTION:
XS GIS Cut Line= 4
       749996.57       629592.64       749908.88       629574.21
       749847.83        629753.3       749573.48       629861.72
#Sta/Elev= 30
3399.345 2424.953408.325 2419.163433.286 2395.423435.761 2392.193447.923 2385.03
3462.702 2383.723507.745 2384.283525.281 2381.063528.392 2381.573531.291 2377.63
3532.705 2374.083538.362 2374.083539.706 2377.46 3540.13 2383.353543.934 2384.23
3563.323 2384.743566.151 2382.563575.344 2385.393595.284 2386.093651.853  2393.8
3665.288 2391.843670.733 2393.42 3680.42 2391.273691.946 2396.65 3696.33  2393.1
3719.735 2397.683732.392 2398.763764.212 2409.143790.517 2416.393805.083 2418.84
#Mann= 3 ,-1 , 0
3399.345     .09       03531.291     .05       03539.706     .06       0
#XS Ineff= 4 ,-1
3399.3453517.149    23903517.5033528.463 2381.573543.2413553.848 2381.57
3553.9193805.083    2390
Permanent Ineff=
       F       F       F       F
Bank Sta=3531.291,3539.706
Skew Angle= 45
Exp/Cntr=0.5,0.3

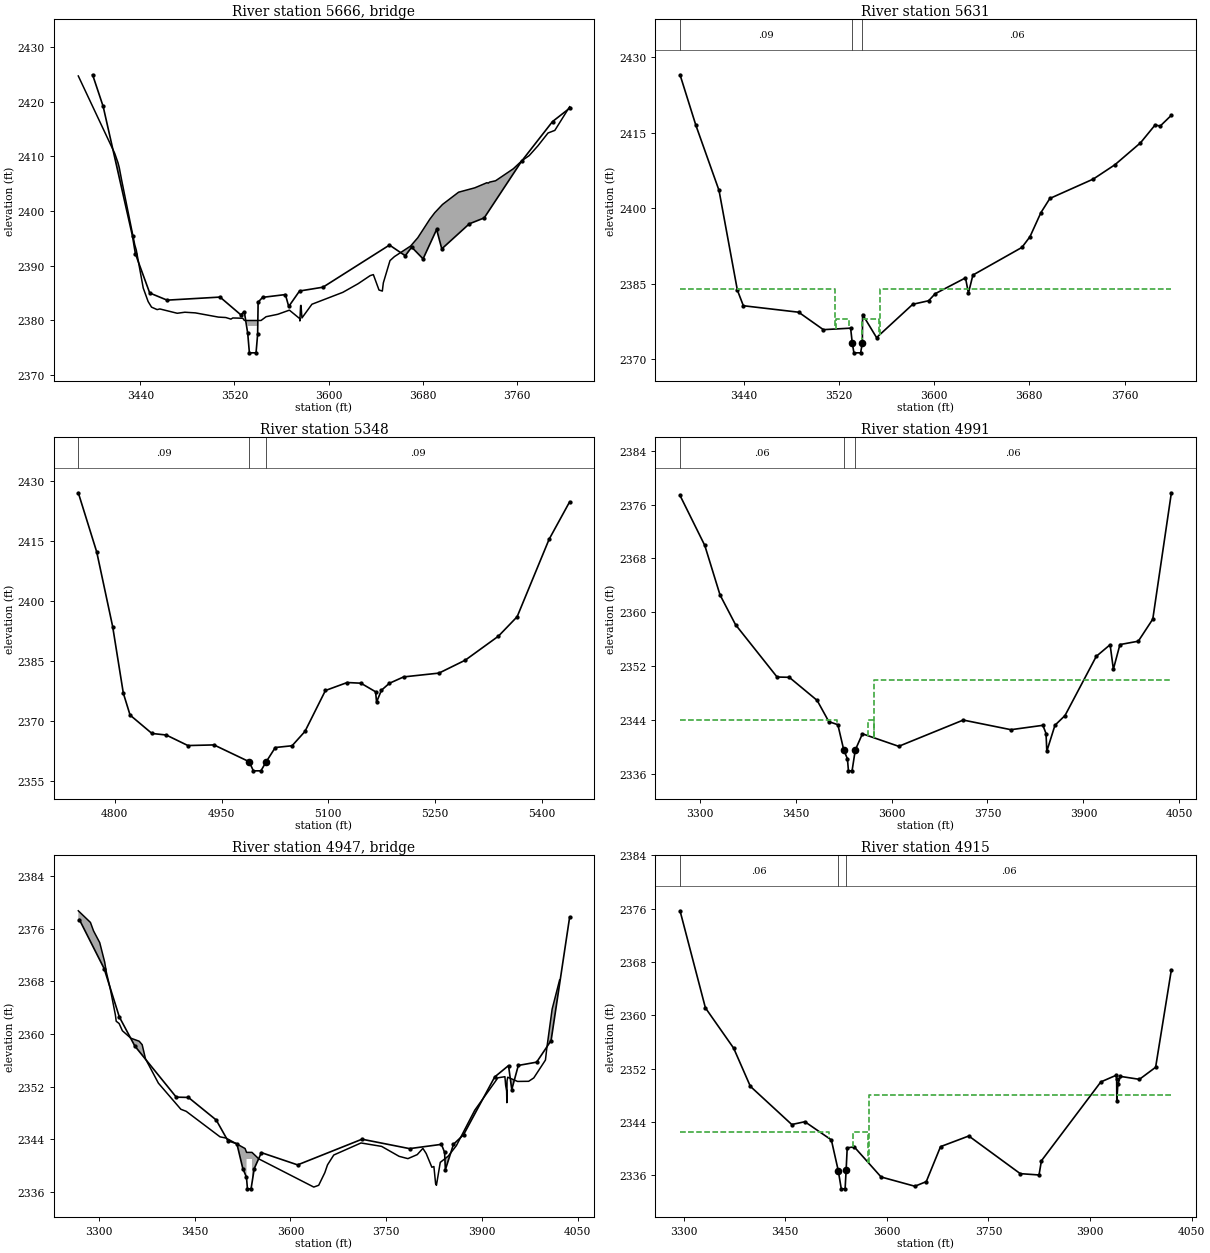
Type RM Length L Ch R = 3 ,5666    ,,,
BEGIN DESCRIPTION:
XS 44 TOR
Structure ID: XS 44
Approximate Survey Structure
END DESCRIPTION:
Bridge Culvert--1,0,-1,-1, 0
Deck Dist Width WeirC Skew NumUp NumDn MinLoCord MaxHiCord MaxSubmerge Is_Ogee
42,22,3,45, 60, 60, , , , 0, 1,1,,
3387.1833418.1543420.9833422.0433423.9533435.1963436.5393442.408 3446.583449.479
3454.217 3456.553471.3293477.8343486.7433506.3313512.6243517.0083518.5633527.049
3528.4633528.4633542.6053542.6053546.9183556.8183566.7173575.5563575.6273576.263
3576.6173577.395 3585.883612.1843625.1953635.4483638.1353642.9433645.772 3646.62
3652.2773656.0253669.8133675.8953686.2183690.3193696.9663710.6143724.4023734.655
3735.9283736.918 3742.083757.1413764.4953770.6473778.0013786.6983792.4963805.083
 2424.73 2410.58 2408.84 2407.95 2405.79 2393.86 2392.85 2385.94 2383.46 2382.44
 2381.99 2382.11 2381.32 2381.51 2381.39 2380.62 2380.54 2380.25 2380.46 2380.41
    2380    2380    2380    2380 2380.69 2381.13 2381.89 2380.33 2379.91 2382.72
 2382.77 2380.46 2382.97 2385.15 2386.73 2388.21 2388.39 2385.57 2385.38 2386.88
 2390.95 2391.68 2393.62 2395.13 2398.55 2399.71 2401.23 2403.47 2404.27  2405.2
 2405.13 2405.31 2405.56 2407.75 2409.23 2410.16 2411.93  2414.3 2414.78 2419.11
  2351.5  2351.5  2351.5  2351.5  2351.5  2351.5  2351.5  2351.5  2351.5  2351.5
  2351.5  2351.5  2351.5  2351.5  2351.5  2351.5  2351.5  2351.5  2351.5  2351.5
  2351.5    2379    2379  2351.5  2351.5  2351.5  2351.5  2351.5  2351.5  2351.5
  2351.5  2351.5  2351.5  2351.5  2351.5  2351.5  2351.5  2351.5  2351.5  2351.5
  2351.5  2351.5  2351.5  2351.5  2351.5  2351.5  2351.5  2351.5  2351.5  2351.5
  2351.5  2351.5  2351.5  2351.5  2351.5  2351.5  2351.5  2351.5  2351.5  2351.5
3387.1833418.1543420.9833422.0433423.9533435.1963436.5393442.408 3446.583449.479
3454.217 3456.553471.3293477.8343486.7433506.3313512.6243517.0083518.5633527.049
3528.4633528.4633542.6053542.6053546.9183556.8183566.7173575.5563575.6273576.263
3576.6173577.395 3585.883612.1843625.1953635.4483638.1353642.9433645.772 3646.62
3652.2773656.0253669.8133675.8953686.2183690.3193696.9663710.6143724.4023734.655
3735.9283736.918 3742.083757.1413764.4953770.6473778.0013786.6983792.4963805.083
 2424.73 2410.58 2408.84 2407.95 2405.79 2393.86 2392.85 2385.94 2383.46 2382.44
 2381.99 2382.11 2381.32 2381.51 2381.39 2380.62 2380.54 2380.25 2380.46 2380.41
    2380    2380    2380    2380 2380.69 2381.13 2381.89 2380.33 2379.91 2382.72
 2382.77 2380.46 2382.97 2385.15 2386.73 2388.21 2388.39 2385.57 2385.38 2386.88
 2390.95 2391.68 2393.62 2395.13 2398.55 2399.71 2401.23 2403.47 2404.27  2405.2
 2405.13 2405.31 2405.56 2407.75 2409.23 2410.16 2411.93  2414.3 2414.78 2419.11
  2351.5  2351.5  2351.5  2351.5  2351.5  2351.5  2351.5  2351.5  2351.5  2351.5
  2351.5  2351.5  2351.5  2351.5  2351.5  2351.5  2351.5  2351.5  2351.5  2351.5
  2351.5    2379    2379  2351.5  2351.5  2351.5  2351.5  2351.5  2351.5  2351.5
  2351.5  2351.5  2351.5  2351.5  2351.5  2351.5  2351.5  2351.5  2351.5  2351.5
  2351.5  2351.5  2351.5  2351.5  2351.5  2351.5  2351.5  2351.5  2351.5  2351.5
  2351.5  2351.5  2351.5  2351.5  2351.5  2351.5  2351.5  2351.5  2351.5  2351.5
BR Coef= 1 , 1 , 0 ,1.25, 0 ,,,0.8,0,2,0,
WSPro=,,,, 1 ,,,, 0 ,,,, 0 ,,,,-1 ,-1 ,-1 , 0 , 0 , 0 , 0 , 0
BC Design=,, 0 ,, 0 ,,,,,,
BC HTab HWMax=2424.95

Type RM Length L Ch R = 1 ,5631    ,283,283,283
BEGIN DESCRIPTION:
XS 43
END DESCRIPTION:
XS GIS Cut Line= 6
       750001.48       629528.42       749889.55        629510.1
       749855.97       629555.89       749826.46        629643.4
       749809.16       629704.45       749568.41       629795.72
#Sta/Elev= 30
3386.688 2426.563399.981 2416.523419.427 2403.563434.842 2383.723439.863 2380.62
3486.319 2379.333507.038 2375.863529.948 2376.163531.291 2373.253532.705 2371.25
3538.362 2371.253539.776 2373.253539.989 2378.873551.727 2374.283582.132 2380.91
3595.426 2381.613600.941 2383.013626.397 2386.163628.872 2383.153632.619 2386.72
3673.773 2392.223680.562 2394.363689.754 2399.153697.249 2401.963733.736 2405.82
3751.908 2408.673773.334 2413.023785.567 2416.563789.951 2416.373799.285 2418.51
#Mann= 3 ,-1 , 0
3386.688     .09       03531.291     .05       03539.776     .06       0
#XS Ineff= 4 ,-1
3386.6883517.149    23843517.8563528.463    23783539.7763553.919    2378
3554.2723799.285    2384
Permanent Ineff=
       F       F       F       F
Bank Sta=3531.291,3539.776
Skew Angle= 45
Exp/Cntr=0.5,0.3

Type RM Length L Ch R = 1 ,5348    ,357,357,357
BEGIN DESCRIPTION:
XS 42
END DESCRIPTION:
XS GIS Cut Line= 5
       750042.26       629362.48       749942.41        629335.4
        749835.8       629328.63       749707.18       629328.63
       749361.94       629260.94
#Sta/Elev= 30
  4748.6    2427  4774.5 2412.23  4796.9 2393.62  4811.9 2376.99  4821.4 2371.52
  4852.1 2366.94  4872.2 2366.55  4902.7 2363.92  4939.3 2364.08  4988.8 2359.89
  4994.7 2357.61  5005.3 2357.61  5012.8 2359.89  5025.5 2363.43  5049.1 2363.87
  5067.2 2367.44    5096 2377.66  5126.6 2379.65  5145.9 2379.48  5166.5 2377.34
  5167.9 2374.78  5174.7 2377.72  5185.8 2379.45  5205.9 2381.05  5255.6    2382
  5292.5 2385.22  5339.2 2391.22  5365.5 2396.07  5410.4 2415.39  5439.3 2424.75
#Mann= 3 ,-1 , 0
  4748.6     .09       0  4988.8     .05       0  5012.8     .09       0
Bank Sta=4988.8,5012.8
Exp/Cntr=0.5,0.3

Type RM Length L Ch R = 1 ,4991    ,76,76,76
BEGIN DESCRIPTION:
XS 41
END DESCRIPTION:
XS GIS Cut Line= 6
       750106.57       629200.01       749899.42       629144.28
       749882.33       629016.72        749827.1       628943.08
       749786.33       628832.62       749270.56       628704.16
#Sta/Elev= 30
 3269.52 2377.353308.199 2369.933332.029 2362.583356.282 2358.163421.195 2350.39
3440.216 2350.353483.773 2346.923502.017 2343.773516.159 2343.313525.422 2339.55
 3531.15 2338.233532.705 2336.463538.362 2336.463543.383 2339.553554.555 2341.96
3611.265  2340.13712.099    23443786.627 2342.573836.549 2343.223841.499    2342
3842.701 2339.373855.429 2343.233871.127 2344.673919.988 2353.463941.625 2355.19
3946.717 2351.553956.969 2355.213985.678 2355.714008.305 2358.994037.368 2377.75
#Mann= 3 ,-1 , 0
 3269.52     .06       03525.422     .05       03543.383     .06       0
#XS Ineff= 3 ,-1
 3269.52 3514.67    2344 3563.11  3572.5    2344    3573 4037.37    2350
Permanent Ineff=
       F       F       F
Bank Sta=3525.422,3543.383
Skew Angle= 45
Exp/Cntr=0.5,0.3

Type RM Length L Ch R = 3 ,4947    ,,,
BEGIN DESCRIPTION:
XS 40 TOR
Structure ID: XS 40
Approximate Survey Structure
END DESCRIPTION:
Bridge Culvert--1,0,-1,-1, 0
Deck Dist Width WeirC Skew NumUp NumDn MinLoCord MaxHiCord MaxSubmerge Is_Ogee
36,16,3,45, 60, 60, , , , 0, 1,1,,
3267.7523286.7743291.653 3301.343309.1183311.5933317.8863325.8063327.1493331.675
3336.837 3350.063363.1413367.808 3372.973393.1933428.4073436.7513489.7843499.047
3528.9583531.2913531.2913539.7763539.7763550.6663636.5793644.2873653.9043658.075
3667.9043710.5433742.8583770.2223784.0113798.6483807.4873812.6493821.559 3824.74
3827.427  3828.73834.7113847.2263859.9543888.7343925.0083935.968  3937.13938.656
3939.0093939.2923940.4233955.7673973.1623981.1533999.4674001.5174009.932 4021.67
 2378.71 2376.94 2375.65 2373.87  2370.9 2369.43 2366.83  2362.9 2361.92 2361.58
 2360.48 2359.35 2358.89 2358.36 2356.22 2352.52 2348.55 2348.24 2344.36 2344.18
 2342.59    2342    2342    2342    2342    2341 2336.73    2337 2338.92  2340.1
  2341.6 2343.43 2342.91  2341.4 2341.05 2341.66 2342.61 2341.83 2339.74 2339.85
 2337.24    2337 2340.48 2341.44 2343.03 2348.41 2353.33  2353.5  2352.2 2351.34
 2349.55 2352.88 2353.42 2352.78  2352.8 2353.31 2356.03 2357.78 2363.77 2368.21
    2315    2315    2315    2315    2315    2315    2315    2315    2315    2315
    2315    2315    2315    2315    2315    2315    2315    2315    2315    2315
    2315    2315    2341    2341    2315    2315    2315    2315    2315    2315
    2315    2315    2315    2315    2315    2315    2315    2315    2315    2315
    2315    2315    2315    2315    2315    2315    2315    2315    2315    2315
    2315    2315    2315    2315    2315    2315    2315    2315    2315    2315
3267.7523286.7743291.653 3301.343309.1183311.5933317.8863325.8063327.1493331.675
3336.837 3350.063363.1413367.808 3372.973393.1933428.4073436.7513489.7843499.047
3528.9583531.2913531.2913539.7763539.7763550.6663636.5793644.2873653.9043658.075
3667.9043710.5433742.8583770.2223784.0113798.6483807.4873812.6493821.559 3824.74
3827.427  3828.73834.7113847.2263859.9543888.7343925.0083935.968  3937.13938.656
3939.0093939.2923940.4233955.7673973.1623981.1533999.4674001.5174009.932 4021.67
 2378.71 2376.94 2375.65 2373.87  2370.9 2369.43 2366.83  2362.9 2361.92 2361.58
 2360.48 2359.35 2358.89 2358.36 2356.22 2352.52 2348.55 2348.24 2344.36 2344.18
 2342.59    2342    2342    2342    2342    2341 2336.73    2337 2338.92  2340.1
  2341.6 2343.43 2342.91  2341.4 2341.05 2341.66 2342.61 2341.83 2339.74 2339.85
 2337.24    2337 2340.48 2341.44 2343.03 2348.41 2353.33  2353.5  2352.2 2351.34
 2349.55 2352.88 2353.42 2352.78  2352.8 2353.31 2356.03 2357.78 2363.77 2368.21
    2315    2315    2315    2315    2315    2315    2315    2315    2315    2315
    2315    2315    2315    2315    2315    2315    2315    2315    2315    2315
    2315    2315    2341    2341    2315    2315    2315    2315    2315    2315
    2315    2315    2315    2315    2315    2315    2315    2315    2315    2315
    2315    2315    2315    2315    2315    2315    2315    2315    2315    2315
    2315    2315    2315    2315    2315    2315    2315    2315    2315    2315
Abutment Skew #Up #Dn= , 2 , 2
3531.2913531.998
    2341    2336
3531.2913531.998
    2341 2335.75
Abutment Skew #Up #Dn= , 2 , 2
3539.0693539.776
    2336    2341
3539.0693539.776
 2335.75    2341
BR Coef= 1 , 1 , 0 ,1.25, 0 ,,,0.8,0,2,0,
WSPro=,,,, 1 ,,,, 0 ,,,, 0 ,,,,-1 ,-1 ,-1 , 0 , 0 , 0 , 0 , 0
BC Design=,, 0 ,, 0 ,,,,,,
BC HTab HWMax=2377.75

Type RM Length L Ch R = 1 ,4915    ,320,320,320
BEGIN DESCRIPTION:
XS 39
END DESCRIPTION:
XS GIS Cut Line= 6
       750103.18        629137.4        749975.7       629098.26
         749906.       628948.34        749862.6       628899.69
       749849.45       628780.02       749323.02       628658.47
#Sta/Elev= 30
3294.693 2375.67 3332.17  2361.13373.889 2355.053398.497 2349.333459.661  2343.6
3478.965 2344.023518.068 2341.293528.251 2336.693532.705 2333.953538.362 2333.95
3539.847 2336.733541.473  2340.13551.797 2340.253591.466 2335.733641.317 2334.34
3658.146 2335.033679.218 2340.283720.938 2341.883796.881 2336.233824.599 2336.03
3828.135 2338.163915.816 2349.993938.443 2350.993939.221 2350.363939.433 2347.16
3940.918 2349.623944.807 2350.823972.809 2350.383996.709 2352.194019.973 2366.82
#Mann= 3 ,-1 , 0
3294.693     .06       03528.251     .05       03539.847     .06       0
#XS Ineff= 3 ,-1
 3294.69 3514.39 2342.45 3550.45 3572.87 2342.45    3573 4019.97    2348
Permanent Ineff=
       F       F       F
Bank Sta=3528.251,3539.847
Skew Angle= 45
Exp/Cntr=0.5,0.3