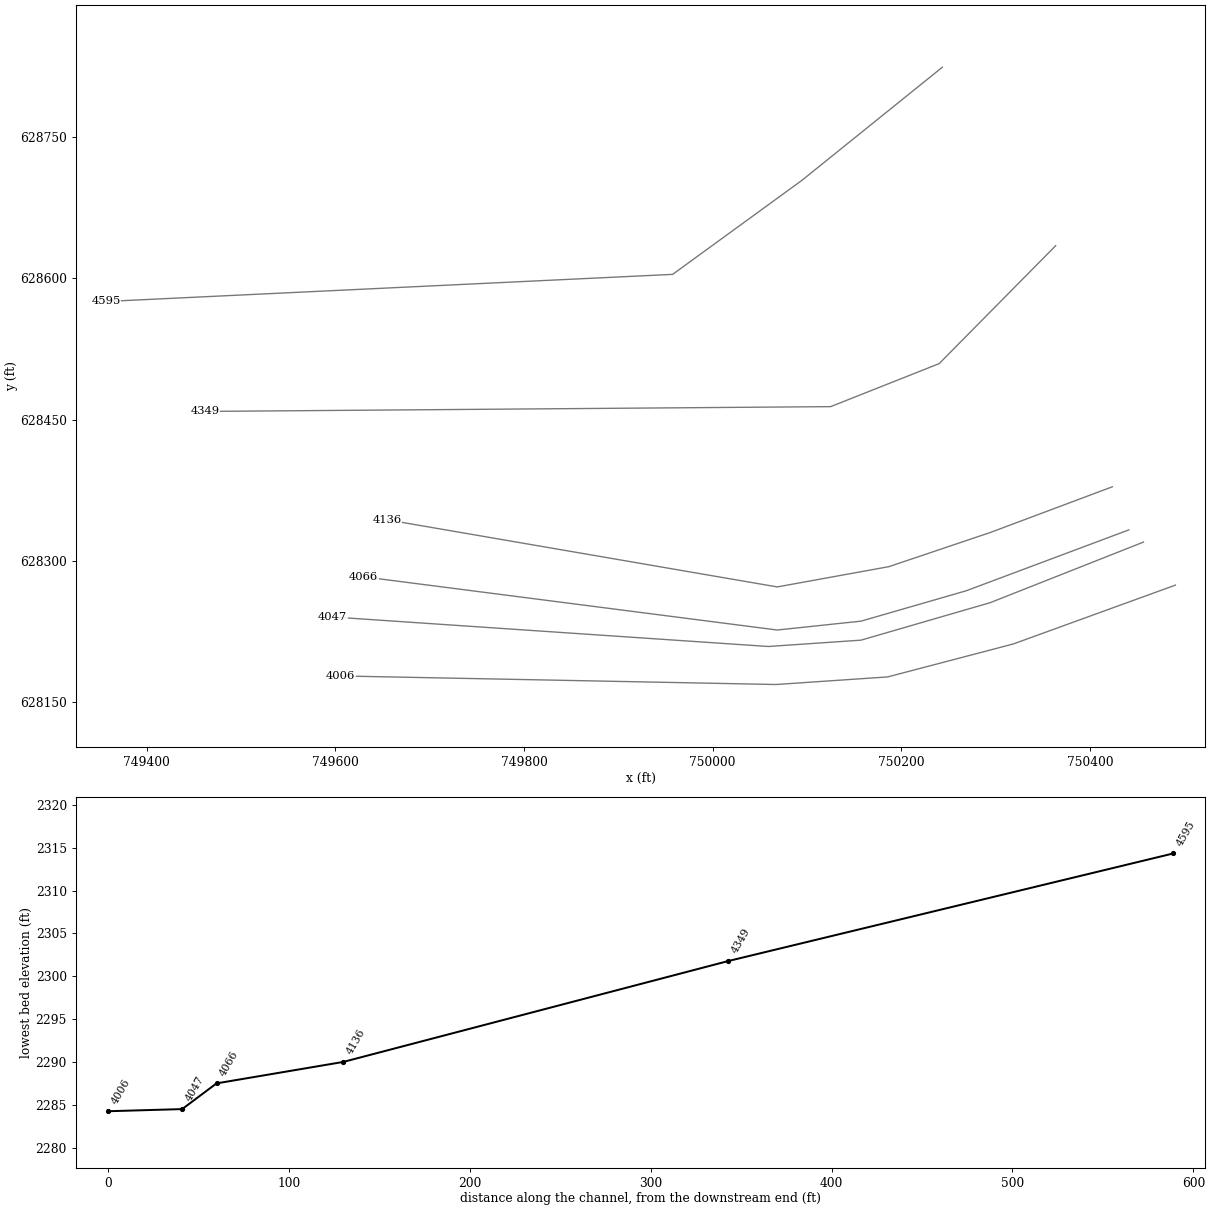
HEC-RAS study lds_fisher_crk.prj: Fisher Creek Limited Detail Study

--- lds_fisher_crk.g01 (geometry) --- (continued)

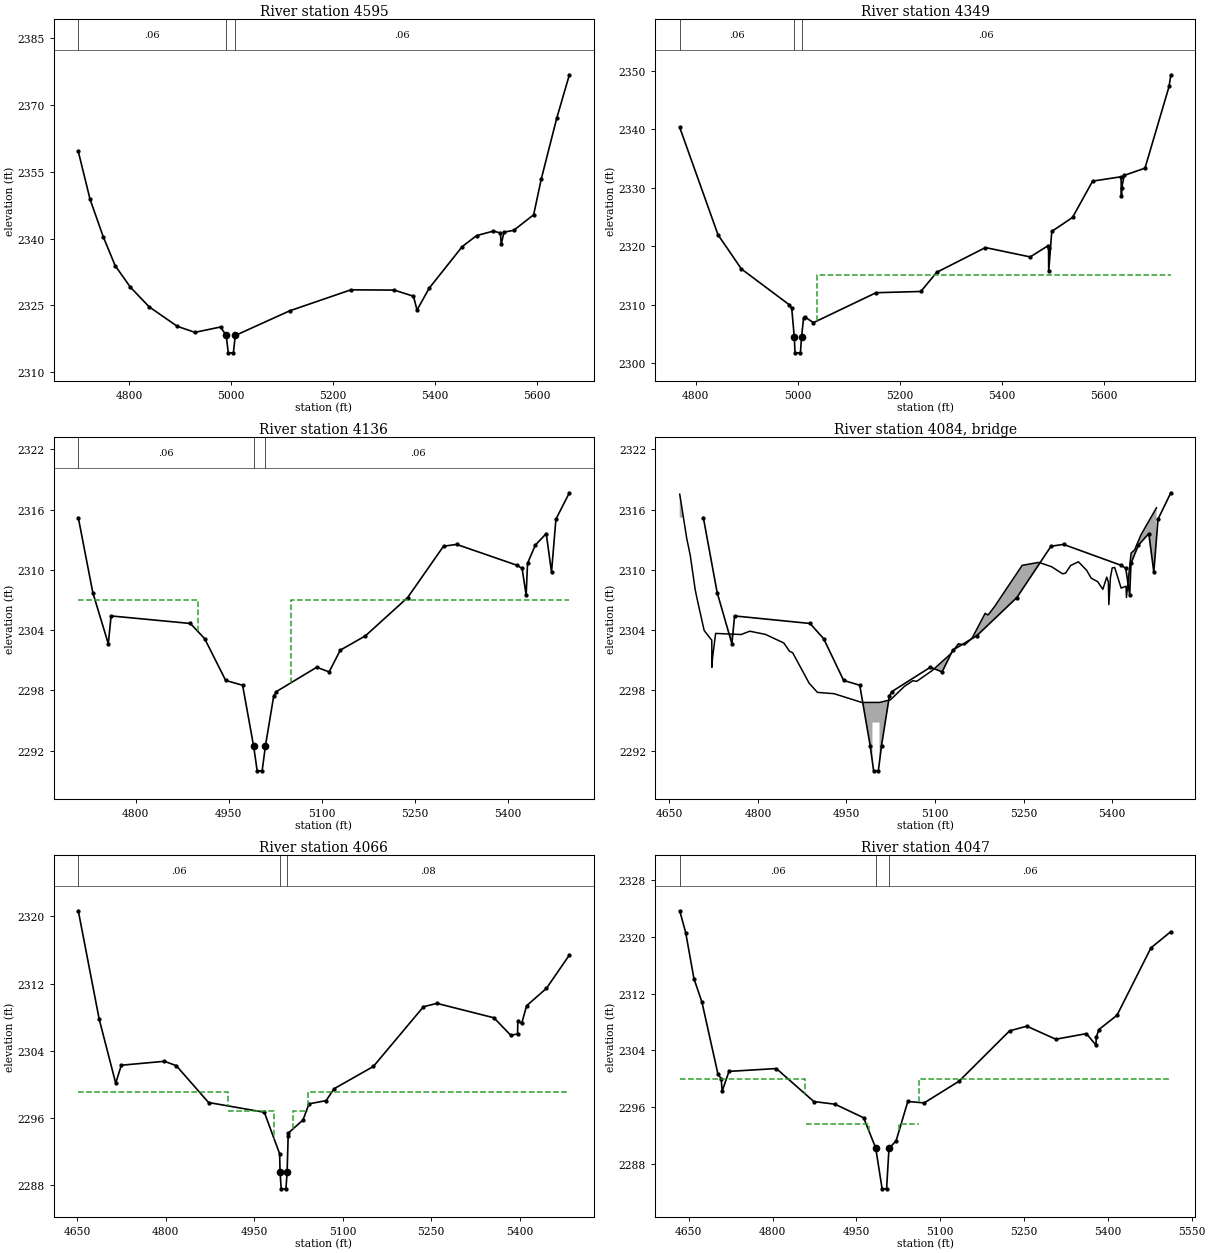
Type RM Length L Ch R = 1 ,4595    ,246,246,246
BEGIN DESCRIPTION:
XS 38
END DESCRIPTION:
XS GIS Cut Line= 4
       750243.65       628824.32       750094.72       628704.16
       749957.64       628604.31       749356.87       628575.54
#Sta/Elev= 30
  4700.8 2359.59  4723.8 2348.86  4749.6 2340.44  4773.1 2333.92  4802.9 2329.08
  4839.9 2324.65  4894.7  2320.3  4929.4 2318.93  4979.7 2320.14  4990.7 2318.23
  4994.7 2314.33  5004.8 2314.33  5008.4 2318.23  5115.3 2323.78    5235 2328.49
  5319.9 2328.43  5357.7 2327.05  5364.6 2323.94  5388.4 2328.85  5453.3 2338.21
  5481.3 2340.67  5514.4 2341.69  5528.1 2341.25  5529.6 2338.74  5535.1 2341.44
  5554.3 2341.87  5593.2 2345.36  5607.9 2353.28  5638.3    2367  5663.2 2376.81
#Mann= 3 ,-1 , 0
  4700.8     .06       0  4990.7     .05       0  5008.4     .06       0
Bank Sta=4990.7,5008.4
Exp/Cntr=0.3,0.1

Type RM Length L Ch R = 1 ,4349    ,213,213,213
BEGIN DESCRIPTION:
XS 37
END DESCRIPTION:
XS GIS Cut Line= 4
        750363.8       628634.77       750240.26       628509.54
       750125.19       628463.85       749461.79       628458.77
#Sta/Elev= 30
  4768.6 2340.27  4843.7 2321.94  4889.5 2316.11  4983.5 2309.99  4988.3 2309.36
  4993.3 2304.44  4994.7 2301.78  5005.3 2301.78  5007.5 2304.44  5011.5 2307.72
  5013.7 2307.92  5030.9 2306.94  5153.7 2312.05  5241.5 2312.26  5272.6 2315.53
  5368.2 2319.76    5456 2318.16  5491.7 2320.11    5492 2319.69  5492.3 2315.72
  5498.3 2322.52    5539  2324.9  5578.4 2331.11  5634.2 2331.85    5635 2328.51
  5635.3 2329.91  5640.5 2332.09  5681.1 2333.32  5728.4 2347.28  5731.8 2349.27
#Mann= 3 ,-1 , 0
  4768.6     .06       0  4993.3     .05       0  5007.5     .06       0
#XS Ineff= 2 , 0
       0                    5038       0    2315
Permanent Ineff=
       F       F
Bank Sta=4993.3,5007.5
Exp/Cntr=0.5,0.3

Type RM Length L Ch R = 1 ,4136    ,70,70,70
BEGIN DESCRIPTION:
XS 36
END DESCRIPTION:
XS GIS Cut Line= 5
       750423.88       628378.73       750294.67       628330.27
         750187.       628293.93       750068.55        628272.4
       749654.72       628343.69
#Sta/Elev= 30
  4707.5 2315.21  4730.9 2307.75  4755.9 2302.65  4760.4 2305.42  4888.2 2304.67
  4911.3 2303.16  4945.2    2299  4972.5 2298.52  4990.3 2292.45    4996    2290
    5004    2290  5009.4 2292.51  5022.6 2297.42  5026.7 2297.88    5092 2300.31
  5112.1 2299.85    5130 2302.01  5170.6 2303.44  5238.7 2307.25  5296.5 2312.36
  5317.7 2312.54  5415.2 2310.46  5423.2 2310.16  5429.8  2307.5    5432 2310.65
  5444.6 2312.47  5462.2 2313.62  5470.7 2309.78  5477.8 2315.05  5499.5 2317.68
#Mann= 3 ,-1 , 0
  4707.5     .06       0  4990.3    .045       0  5009.4     .06       0
#XS Ineff= 4 ,-1
  4707.5    4900    2307    4900  4970.3 2296.85  5029.4    5050 2296.86
    5050  5499.5    2307
Permanent Ineff=
       F       F       F       F
Bank Sta=4990.3,5009.4
Exp/Cntr=0.5,0.3

Type RM Length L Ch R = 3 ,4084    ,,,
BEGIN DESCRIPTION:
XS 35 TOR
Structure ID: XS 35 TOR
Approximate Survey Structure
END DESCRIPTION:
Bridge Culvert--1,0,-1,-1, 0
Deck Dist Width WeirC Skew NumUp NumDn MinLoCord MaxHiCord MaxSubmerge Is_Ogee
48,8,3,0, 60, 60, , , , 0, 1,1,,
  4667.5  4679.4  4685.3  4693.8  4697.3  4708.9  4721.8    4722    4723  4728.3
  4771.4  4786.2  4812.8  4843.8  4853.4  4858.9  4886.8  4900.8    4929  4975.8
    4994    4994    5006    5006  5024.7  5048.2  5062.5    5069  5095.1  5126.6
  5139.6  5150.2    5163  5184.9  5189.8  5200.6  5247.7  5275.8  5297.5  5315.9
    5321  5329.8  5342.9  5356.8  5364.6  5375.6  5384.3  5390.9  5393.6  5394.5
  5397.2  5400.2  5404.4  5415.3  5423.6  5424.3  5432.2  5438.3  5448.6  5475.2
 2317.54 2313.13 2311.46    2308 2307.02 2303.97    2303 2300.31  2301.2 2303.68
 2303.57  2303.9 2303.58 2302.73 2301.91 2301.75 2298.72 2297.81 2297.68 2296.81
 2296.81 2296.81 2296.81 2296.81 2297.08 2298.41 2298.97 2298.91 2299.98 2301.65
 2302.65 2302.53 2303.23 2305.68 2305.51 2306.33 2310.46 2310.75 2310.32 2309.62
 2309.67 2310.44 2310.81 2309.97 2309.18 2308.83 2308.07 2309.28 2308.82 2306.55
 2309.26  2310.2 2310.24 2308.19 2308.38 2307.26 2311.68 2312.01 2313.46 2316.19
    2267    2267    2267    2267    2267    2267    2267    2267    2267    2267
    2267    2267    2267    2267    2267    2267    2267    2267    2267    2267
    2267 2294.81 2294.81    2267    2267    2267    2267    2267    2267    2267
    2267    2267    2267    2267    2267    2267    2267    2267    2267    2267
    2267    2267    2267    2267    2267    2267    2267    2267    2267    2267
    2267    2267    2267    2267    2267    2267    2267    2267    2267    2267
  4667.5  4679.4  4685.3  4693.8  4697.3  4708.9  4721.8    4722    4723  4728.3
  4771.4  4786.2  4812.8  4843.8  4853.4  4858.9  4886.8  4900.8    4929  4975.8
    4994    4994    5006    5006  5024.7  5048.2  5062.5    5069  5095.1  5126.6
  5139.6  5150.2    5163  5184.9  5189.8  5200.6  5247.7  5275.8  5297.5  5315.9
    5321  5329.8  5342.9  5356.8  5364.6  5375.6  5384.3  5390.9  5393.6  5394.5
  5397.2  5400.2  5404.4  5415.3  5423.6  5424.3  5432.2  5438.3  5448.6  5475.2
 2317.54 2313.13 2311.46    2308 2307.02 2303.97    2303 2300.31  2301.2 2303.68
 2303.57  2303.9 2303.58 2302.73 2301.91 2301.75 2298.72 2297.81 2297.68 2296.81
 2296.81 2296.81 2296.81 2296.81 2297.08 2298.41 2298.97 2298.91 2299.98 2301.65
 2302.65 2302.53 2303.23 2305.68 2305.51 2306.33 2310.46 2310.75 2310.32 2309.62
 2309.67 2310.44 2310.81 2309.97 2309.18 2308.83 2308.07 2309.28 2308.82 2306.55
 2309.26  2310.2 2310.24 2308.19 2308.38 2307.26 2311.68 2312.01 2313.46 2316.19
    2267    2267    2267    2267    2267    2267    2267    2267    2267    2267
    2267    2267    2267    2267    2267    2267    2267    2267    2267    2267
    2267 2294.81 2294.81    2267    2267    2267    2267    2267    2267    2267
    2267    2267    2267    2267    2267    2267    2267    2267    2267    2267
    2267    2267    2267    2267    2267    2267    2267    2267    2267    2267
    2267    2267    2267    2267    2267    2267    2267    2267    2267    2267
BR Coef= 1 , 1 , 0 ,1.25, 0 ,,,0.8,0,2,0,
WSPro=,,,, 1 ,,,, 0 ,,,, 0 ,,,,-1 ,-1 ,-1 , 0 , 0 , 0 , 0 , 0
BC Design=,, 0 ,, 0 ,,,,,,
BC HTab HWMax=2317.68

Type RM Length L Ch R = 1 ,4066    ,19,19,19
BEGIN DESCRIPTION:
XS 34
END DESCRIPTION:
XS GIS Cut Line= 5
       750441.38       628332.96        750269.1       628268.36
       750157.39       628236.05       750068.55       628226.63
       749629.77       628283.16
#Sta/Elev= 30
  4652.2 2320.68  4687.7 2307.72  4715.6 2300.11  4725.1 2302.25  4798.1 2302.72
  4818.2  2302.2  4872.9  2297.8  4967.4 2296.64  4993.4 2291.67    4994  2289.5
    4996  2287.5    5004  2287.5    5006  2289.5  5007.8 2293.84  5008.3 2294.17
  5032.9 2295.72  5043.1 2297.64  5072.1 2298.03  5085.4 2299.44  5152.1  2302.1
    5237 2309.23  5259.8 2309.63  5356.4 2307.91  5385.1 2305.81  5396.4 2305.99
  5396.9  2307.5  5403.4 2307.25  5411.8 2309.35  5445.4 2311.43  5484.2  2315.4
#Mann= 3 ,-1 , 0
  4652.2     .06       0    4994    .052       0    5006     .08       0
#XS Ineff= 4 ,-1
  4652.2    4905    2299    4905    4984  2296.8    5016  5041.5  2296.8
  5041.8  5484.2    2299
Permanent Ineff=
       F       F       F       F
Bank Sta=4994,5006
Exp/Cntr=0.5,0.3

Type RM Length L Ch R = 1 ,4047    ,41,41,41
BEGIN DESCRIPTION:
XS 32
END DESCRIPTION:
XS GIS Cut Line= 5
       750456.88         628320.       750294.42       628255.69
       750157.39       628215.87       750059.13       628209.14
       749597.18       628240.46
#Sta/Elev= 30
  4633.8 2323.68  4644.5 2320.59  4659.2 2314.13  4673.6 2310.79    4702 2300.74
  4708.1 2299.98  4709.7 2298.24  4721.9 2301.05  4806.7 2301.45  4873.8  2296.8
  4911.9 2296.42    4963 2294.51  4984.6 2290.24    4996  2284.5    5004  2284.5
  5008.3 2290.21    5021 2291.25    5042 2296.81  5071.3 2296.61  5133.6 2299.66
  5224.1 2306.76    5255 2307.42  5306.8 2305.58  5361.7 2306.37  5378.7 2304.75
  5379.3 2305.86  5383.9 2306.94  5416.4 2308.96  5477.1 2318.45  5512.7 2320.74
#Mann= 3 ,-1 , 0
  4633.8     .06       0  4984.6    .055       0  5008.3     .06       0
#XS Ineff= 4 ,-1
 4633.87 4858.64    2300    4859 4972.56 2293.63    5027    5062 2293.63
  5062.5  5512.7    2300
Permanent Ineff=
       F       F       F       F
Bank Sta=4984.6,5008.3
Exp/Cntr=0.5,0.3

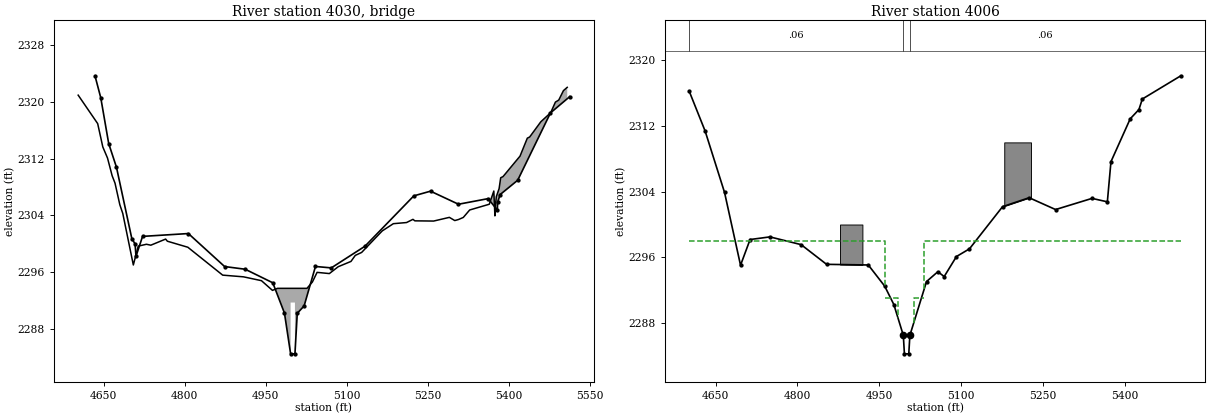
Type RM Length L Ch R = 3 ,4030    ,,,
BEGIN DESCRIPTION:
XS 31 TOR
Structure ID: XS 31
Approximate Survey Structure
END DESCRIPTION:
Bridge Culvert--1,0,-1,-1, 0
Deck Dist Width WeirC Skew NumUp NumDn MinLoCord MaxHiCord MaxSubmerge Is_Ogee
12,10,3,0, 60, 60, , , , 0, 1,1,,
  4602.7  4638.8  4648.3    4657  4665.6  4670.9  4679.8  4685.3  4704.8  4713.9
  4729.1  4737.2  4764.6  4767.8  4805.7  4870.2  4908.8    4942  4962.4  4971.6
    4996    4996    5004    5004  5026.3  5036.3    5045  5067.7  5084.2  5107.7
  5115.7  5127.5  5165.6  5186.2  5210.6  5222.5    5226  5260.8  5289.9  5299.9
  5306.9  5315.7  5327.5  5363.8  5372.2  5374.2  5374.9  5376.8    5382  5384.9
  5389.3  5420.7  5434.2  5438.6  5459.2  5477.4  5486.2  5492.4  5501.1  5508.1
 2320.95 2316.94 2313.65 2312.09 2309.59 2308.55 2305.51 2304.27 2297.02 2299.68
 2299.94 2299.81 2300.67 2300.37 2299.52 2295.59 2295.35 2294.81 2293.44 2293.73
 2293.73 2293.73 2293.73 2293.73 2293.73 2294.62 2295.98 2295.81 2296.78 2297.52
 2298.37 2298.79 2301.82 2302.84    2303 2303.45 2303.24 2303.21 2303.73 2303.28
 2303.43 2303.72 2304.77 2305.58 2307.44 2303.94 2305.19 2306.65 2307.79 2309.31
 2309.48 2312.36 2314.89 2315.06  2317.2 2318.47 2319.97 2320.26 2321.59 2322.05
  2264.5  2264.5  2264.5  2264.5  2264.5  2264.5  2264.5  2264.5  2264.5  2264.5
  2264.5  2264.5  2264.5  2264.5  2264.5  2264.5  2264.5  2264.5  2264.5  2264.5
  2264.5 2291.73 2291.73  2264.5  2264.5  2264.5  2264.5  2264.5  2264.5  2264.5
  2264.5  2264.5  2264.5  2264.5  2264.5  2264.5  2264.5  2264.5  2264.5  2264.5
  2264.5  2264.5  2264.5  2264.5  2264.5  2264.5  2264.5  2264.5  2264.5  2264.5
  2264.5  2264.5  2264.5  2264.5  2264.5  2264.5  2264.5  2264.5  2264.5  2264.5
  4602.7  4638.8  4648.3    4657  4665.6  4670.9  4679.8  4685.3  4704.8  4713.9
  4729.1  4737.2  4764.6  4767.8  4805.7  4870.2  4908.8    4942  4962.4  4971.6
    4996    4996    5004    5004  5026.3  5036.3    5045  5067.7  5084.2  5107.7
  5115.7  5127.5  5165.6  5186.2  5210.6  5222.5    5226  5260.8  5289.9  5299.9
  5306.9  5315.7  5327.5  5363.8  5372.2  5374.2  5374.9  5376.8    5382  5384.9
  5389.3  5420.7  5434.2  5438.6  5459.2  5477.4  5486.2  5492.4  5501.1  5508.1
 2320.95 2316.94 2313.65 2312.09 2309.59 2308.55 2305.51 2304.27 2297.02 2299.68
 2299.94 2299.81 2300.67 2300.37 2299.52 2295.59 2295.35 2294.81 2293.44 2293.73
 2293.73 2293.73 2293.73 2293.73 2293.73 2294.62 2295.98 2295.81 2296.78 2297.52
 2298.37 2298.79 2301.82 2302.84    2303 2303.45 2303.24 2303.21 2303.73 2303.28
 2303.43 2303.72 2304.77 2305.58 2307.44 2303.94 2305.19 2306.65 2307.79 2309.31
 2309.48 2312.36 2314.89 2315.06  2317.2 2318.47 2319.97 2320.26 2321.59 2322.05
  2264.5  2264.5  2264.5  2264.5  2264.5  2264.5  2264.5  2264.5  2264.5  2264.5
  2264.5  2264.5  2264.5  2264.5  2264.5  2264.5  2264.5  2264.5  2264.5  2264.5
  2264.5 2291.73 2291.73  2264.5  2264.5  2264.5  2264.5  2264.5  2264.5  2264.5
  2264.5  2264.5  2264.5  2264.5  2264.5  2264.5  2264.5  2264.5  2264.5  2264.5
  2264.5  2264.5  2264.5  2264.5  2264.5  2264.5  2264.5  2264.5  2264.5  2264.5
  2264.5  2264.5  2264.5  2264.5  2264.5  2264.5  2264.5  2264.5  2264.5  2264.5
BR Coef= 1 , 1 , 0 ,1.25, 0 ,,,0.8,0,2,0,
WSPro=,,,, 1 ,,,, 0 ,,,, 0 ,,,,-1 ,-1 ,-1 , 0 , 0 , 0 , 0 , 0
BC Design=,, 0 ,, 0 ,,,,,,
BC HTab HWMax=2323.68

Type RM Length L Ch R = 1 ,4006    ,175,175,175
BEGIN DESCRIPTION:
XS 30
END DESCRIPTION:
XS GIS Cut Line= 5
       750490.73       628274.31        750318.9       628211.83
       750185.65       628176.83       750067.21       628168.76
       749605.64       628177.84
#Sta/Elev= 30
  4601.7  2316.2  4630.7 2311.38  4666.3  2303.9  4695.6 2295.04  4713.1 2298.17
  4749.5 2298.49  4806.6 2297.55  4853.3 2295.15  4929.8 2295.07  4959.9 2292.49
  4976.7 2290.24    4994  2286.5    4996 2284.25    5004 2284.25    5006  2286.5
  5036.5 2293.05  5057.3 2294.25  5068.9 2293.66  5091.4  2296.1  5115.3 2297.04
  5175.9 2302.17  5224.7 2303.26  5273.1 2301.82  5339.9 2303.18    5368 2302.76
  5374.6 2307.65  5409.9 2312.87  5425.9    2314  5432.1 2315.28  5502.7 2318.11
#Mann= 3 ,-1 , 0
  4601.7     .06       0    4994     .05       0    5006     .06       0
#XS Ineff= 4 ,-1
  4601.7  4959.9    2298  4960.5    4984    2291    5013    5032    2291
  5032.5  5502.7    2298
Permanent Ineff=
       F       F       F       F
#Block Obstruct= 2 ,-1
    4878    4919    2300    5179    5228    2310
Bank Sta=4994,5006
Exp/Cntr=0.5,0.3