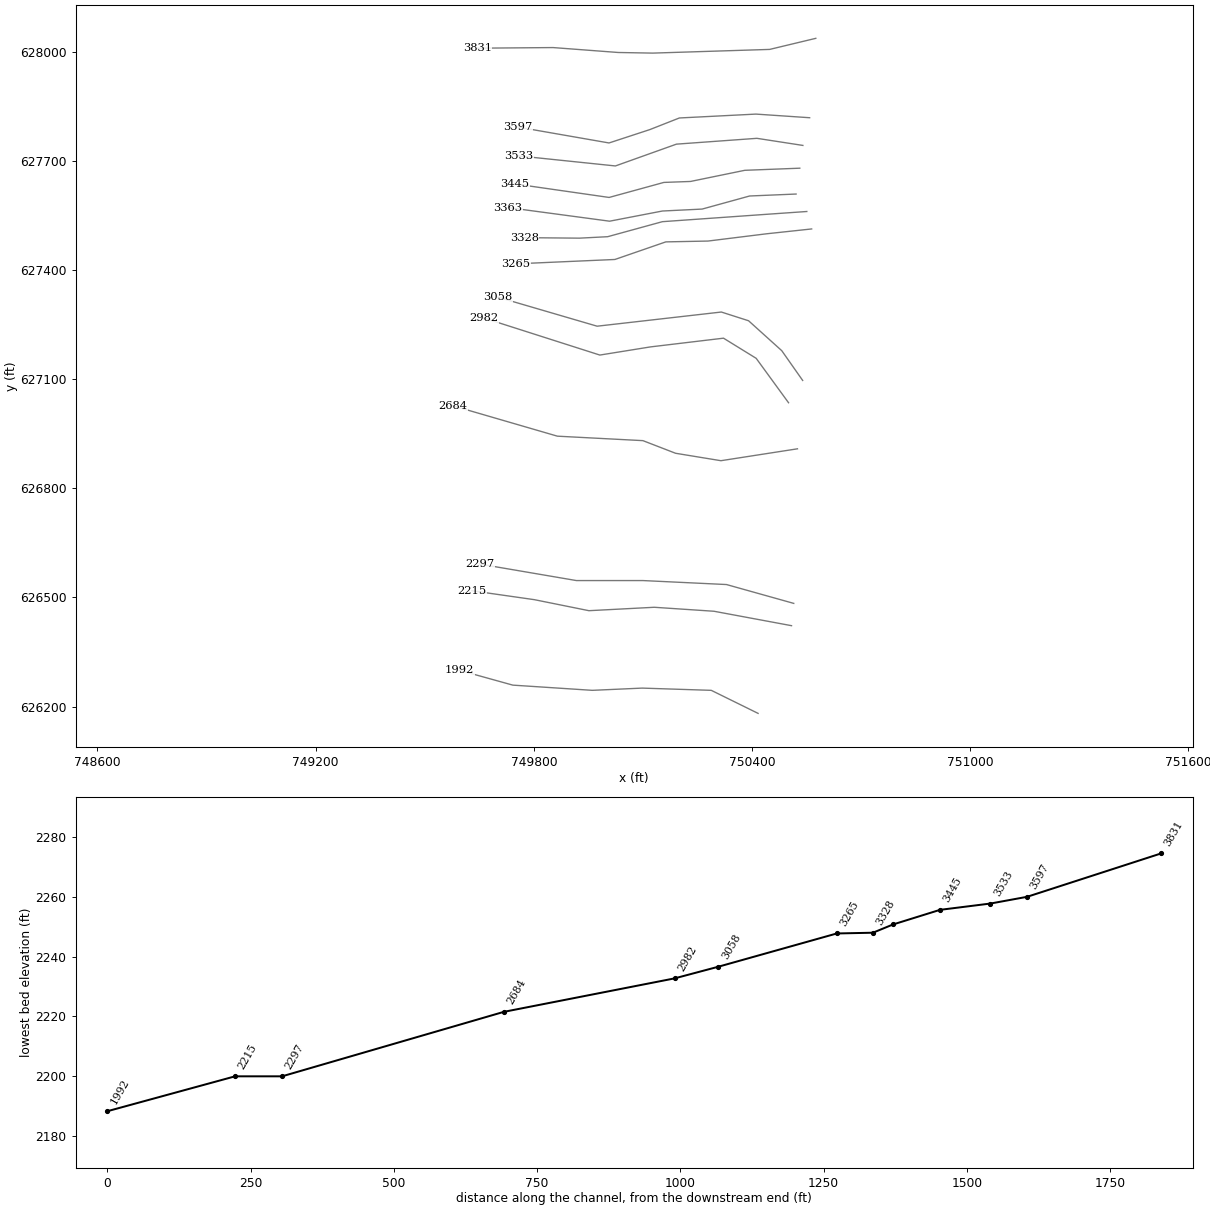
HEC-RAS study lds_fisher_crk.prj: Fisher Creek Limited Detail Study

--- lds_fisher_crk.g01 (geometry) --- (continued)

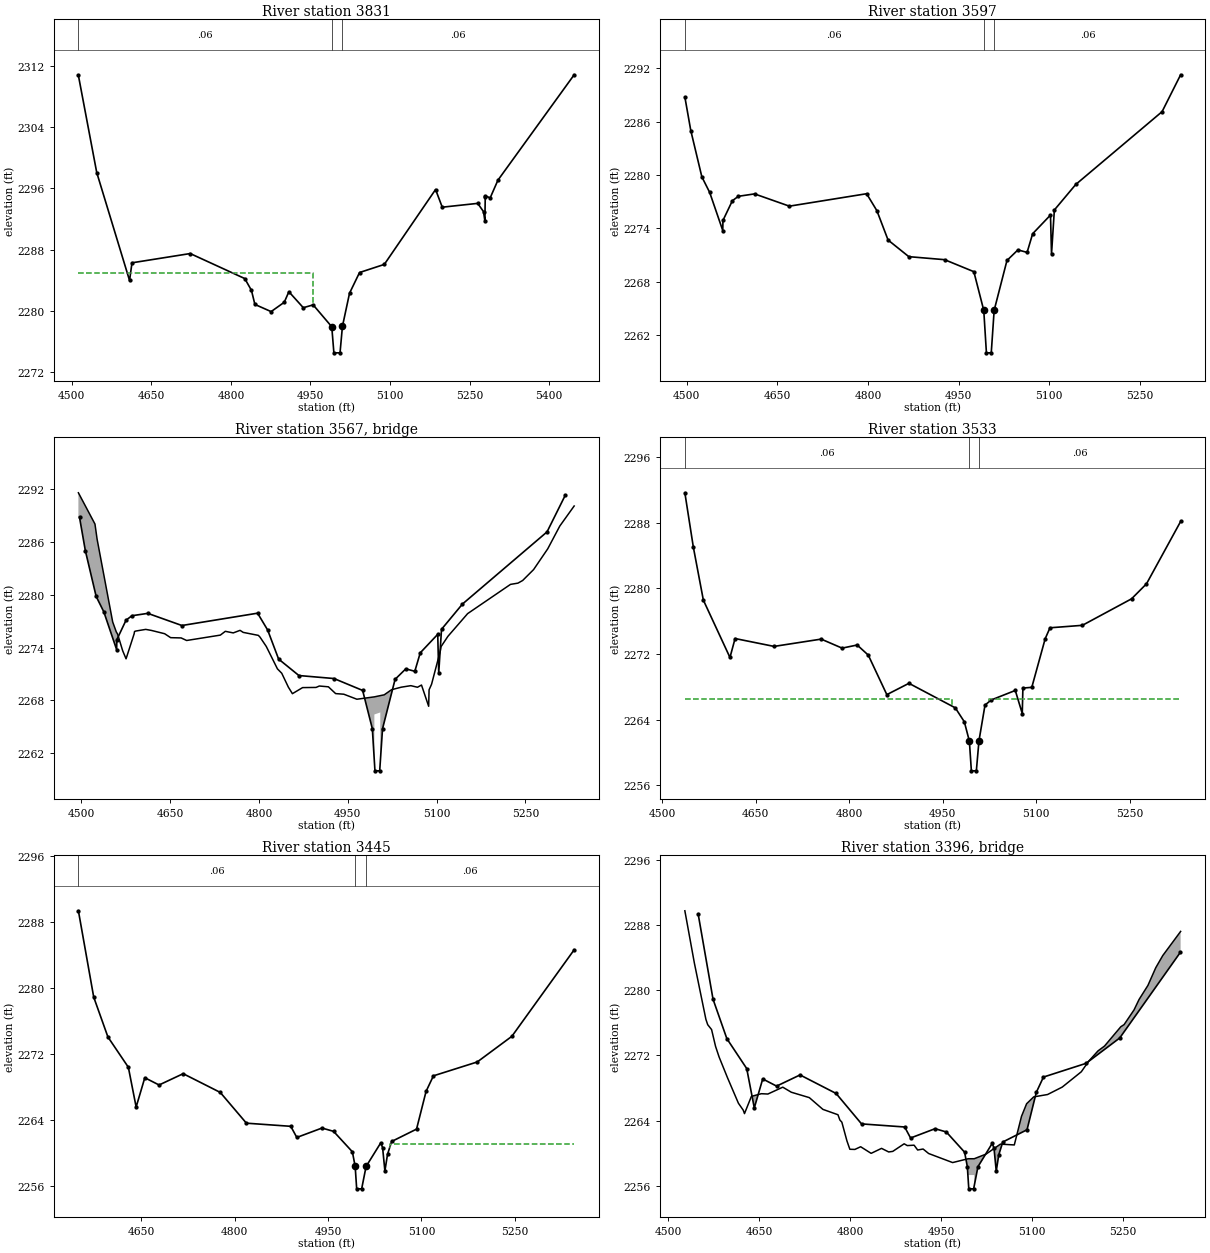
Type RM Length L Ch R = 1 ,3831    ,234,234,234
BEGIN DESCRIPTION:
XS 29
END DESCRIPTION:
XS GIS Cut Line= 6
       750575.35       628037.38       750448.42       628006.92
       750126.88       627996.76       750032.11       627998.46
       749852.72         628012.       749644.56        628010.3
#Sta/Elev= 30
  4512.3 2310.78  4546.9 2298.08  4608.8 2283.97  4613.4 2286.28  4723.2 2287.49
  4826.1 2284.22  4838.7 2282.68  4845.2 2280.84  4875.8  2279.9  4900.6 2281.12
  4909.3  2282.5  4936.5 2280.41  4955.1 2280.78  4990.2 2277.92  4994.2 2274.51
  5005.8 2274.51  5010.3 2277.96  5023.7  2282.3  5042.6 2285.01  5089.3 2286.07
    5186 2295.86  5198.6 2293.55  5265.5 2294.05  5276.5 2292.96    5279 2291.74
  5279.7 2294.92  5279.9 2295.03    5289 2294.77  5303.6 2297.08  5447.4 2310.86
#Mann= 3 ,-1 , 0
  4512.3     .06       0  4990.2     .05       0  5010.3     .06       0
#XS Ineff= 2 , 0
       0    4954    2285               0
Permanent Ineff=
       F       F
Bank Sta=4990.2,5010.3
Exp/Cntr=0.5,0.3

Type RM Length L Ch R = 1 ,3597    ,64,64,64
BEGIN DESCRIPTION:
XS 28
END DESCRIPTION:
XS GIS Cut Line= 6
       750558.42       627819.07        750410.7       627829.05
       750200.16       627818.39       750118.88       627786.41
       750006.72       627749.68       749754.56       627793.68
#Sta/Elev= 30
  4497.1 2288.78  4506.9 2285.01  4525.2  2279.8  4538.2 2278.04  4559.8 2273.76
  4560.1 2274.89  4575.7 2277.11  4585.6 2277.61  4612.4 2277.88    4670  2276.5
  4797.8  2277.9  4814.8 2275.99  4833.3 2272.69  4867.6 2270.82  4926.8 2270.48
  4975.2 2269.13  4991.6 2264.78    4996    2260    5004    2260  5008.8 2264.78
    5030 2270.39  5048.1 2271.58  5063.3  2271.3  5072.5  2273.4    5102  2275.5
  5103.7 2271.12  5108.4 2276.07  5143.8 2278.94  5286.6 2287.13  5317.3 2291.28
#Mann= 3 ,-1 , 0
  4497.1     .06       0  4991.6     .05       0  5008.8     .06       0
#XS Ineff= 2 , 0
       0    4971 2268.16    5029       0 2269.24
Permanent Ineff=
       F       F
Bank Sta=4991.6,5008.8
Exp/Cntr=0.5,0.3

Type RM Length L Ch R = 3 ,3567    ,,,
BEGIN DESCRIPTION:
XS 27 TOR
Structure ID: XS 27
Approximate Survey Structure
END DESCRIPTION:
Bridge Culvert--1,0,-1,-1, 0
Deck Dist Width WeirC Skew NumUp NumDn MinLoCord MaxHiCord MaxSubmerge Is_Ogee
24,12,3,0, 60, 60, , , , 0, 1,1,,
  4495.2  4523.2  4526.8  4553.1  4559.2  4561.4    4570  4575.7  4589.3    4590
    4592  4608.9  4618.6  4640.8    4651  4668.7    4678  4734.9  4743.3  4756.7
  4768.2  4773.5  4799.1  4801.8  4812.5  4831.3  4838.6  4849.8  4856.6  4873.8
  4896.5  4902.1  4917.4  4929.6  4943.4  4965.5    4995    4995    5005    5005
  5011.6    5024  5040.6  5056.6  5067.8  5074.6  5086.7  5087.4  5091.6  5106.6
  5107.6  5119.2  5152.5  5224.9  5237.4  5245.4  5263.9  5287.8  5308.2  5332.4
 2291.57 2288.02  2286.3 2276.91 2275.77 2275.53 2273.63 2272.72 2275.55 2275.82
 2275.87 2276.06 2275.94 2275.57 2275.12 2275.09  2274.8 2275.41 2275.84 2275.66
 2275.95 2275.72 2275.38 2275.19 2274.12 2271.58 2271.08  2269.5 2268.76 2269.45
 2269.47 2269.63 2269.54 2268.77  2268.7 2268.13  2268.4  2268.4 2268.54 2268.54
 2268.63 2269.21  2269.5 2269.67 2269.49 2269.74 2267.33  2269.2 2269.83 2273.68
  2274.1 2275.27 2277.85 2281.17 2281.31 2281.61 2282.85 2285.21  2287.8 2290.07
    2238    2238    2238    2238    2238    2238    2238    2238    2238    2238
    2238    2238    2238    2238    2238    2238    2238    2238    2238    2238
    2238    2238    2238    2238    2238    2238    2238    2238    2238    2238
    2238    2238    2238    2238    2238    2238    2238  2266.4 2266.63    2238
    2238    2238    2238    2238    2238    2238    2238    2238    2238    2238
    2238    2238    2238    2238    2238    2238    2238    2238    2238    2238
  4495.2  4523.2  4526.8  4553.1  4559.2  4561.4    4570  4575.7  4589.3    4590
    4592  4608.9  4618.6  4640.8    4651  4668.7    4678  4734.9  4743.3  4756.7
  4768.2  4773.5  4799.1  4801.8  4812.5  4831.3  4838.6  4849.8  4856.6  4873.8
  4896.5  4902.1  4917.4  4929.6  4943.4  4965.5    4995    4995    5005    5005
  5011.6    5024  5040.6  5056.6  5067.8  5074.6  5086.7  5087.4  5091.6  5106.6
  5107.6  5119.2  5152.5  5224.9  5237.4  5245.4  5263.9  5287.8  5308.2  5332.4
 2291.57 2288.02  2286.3 2276.91 2275.77 2275.53 2273.63 2272.72 2275.55 2275.82
 2275.87 2276.06 2275.94 2275.57 2275.12 2275.09  2274.8 2275.41 2275.84 2275.66
 2275.95 2275.72 2275.38 2275.19 2274.12 2271.58 2271.08  2269.5 2268.76 2269.45
 2269.47 2269.63 2269.54 2268.77  2268.7 2268.13  2268.4  2268.4 2268.54 2268.54
 2268.63 2269.21  2269.5 2269.67 2269.49 2269.74 2267.33  2269.2 2269.83 2273.68
  2274.1 2275.27 2277.85 2281.17 2281.31 2281.61 2282.85 2285.21  2287.8 2290.07
    2238    2238    2238    2238    2238    2238    2238    2238    2238    2238
    2238    2238    2238    2238    2238    2238    2238    2238    2238    2238
    2238    2238    2238    2238    2238    2238    2238    2238    2238    2238
    2238    2238    2238    2238    2238    2238    2238  2266.4 2266.63    2238
    2238    2238    2238    2238    2238    2238    2238    2238    2238    2238
    2238    2238    2238    2238    2238    2238    2238    2238    2238    2238
BR Coef= 1 , 1 , 0 ,1.25, 0 ,,,0.8,0,2,0,
WSPro=,,,, 1 ,,,, 0 ,,,, 0 ,,,,-1 ,-1 ,-1 , 0 , 0 , 0 , 0 , 0
BC Design=,, 0 ,, 0 ,,,,,,
BC HTab HWMax=2291.28

Type RM Length L Ch R = 1 ,3533    ,88,88,88
BEGIN DESCRIPTION:
XS 26
END DESCRIPTION:
XS GIS Cut Line= 5
       750539.81       627742.91       750413.37       627762.42
       750192.17       627746.43       750024.26       627686.46
       749757.95       627714.15
#Sta/Elev= 30
  4536.1 2291.65  4549.7 2285.03  4565.8 2278.56  4608.5 2271.57  4616.7 2273.88
  4679.3 2272.92  4754.9 2273.81  4788.5 2272.71  4812.7 2273.09  4830.5 2271.86
  4860.3 2267.04  4895.8 2268.42  4970.2 2265.43  4984.7 2263.73  4992.8 2261.37
    4996 2257.75    5004 2257.75  5008.2 2261.41  5017.9 2265.77  5027.9 2266.39
  5066.5 2267.55  5077.7 2264.74  5078.7 2267.84    5093 2267.93  5114.5 2273.86
  5122.2 2275.19  5174.2 2275.49  5253.1 2278.72  5277.1 2280.55  5331.9 2288.15
#Mann= 3 ,-1 , 0
  4536.1     .06       0  4992.8     .05       0  5008.2     .06       0
#XS Ineff= 2 , 0
       0    4965 2266.46    5025       0 2266.46
Permanent Ineff=
       F       F
Bank Sta=4992.8,5008.2
Exp/Cntr=0.5,0.3

Type RM Length L Ch R = 1 ,3445    ,82,82,82
BEGIN DESCRIPTION:
XS 25
END DESCRIPTION:
XS GIS Cut Line= 6
       750531.35        627680.3       750380.06       627674.47
       750230.81       627643.82       750157.52       627641.16
       750006.94       627599.85       749747.09       627637.16
#Sta/Elev= 30
  4549.3 2289.35  4573.9 2278.88  4596.7 2274.05  4629.5 2270.38    4642 2265.56
  4655.9 2269.11  4678.8 2268.23  4717.5  2269.6    4777 2267.33    4819  2263.6
  4890.2 2263.22  4899.9 2261.87  4940.3 2263.01  4958.9 2262.61  4989.1 2260.13
  4993.6 2258.35    4996 2255.64    5004 2255.64  5011.1 2258.35  5034.6 2261.21
  5037.6 2260.64  5041.3 2257.81  5045.5 2259.82  5052.1 2261.38  5092.1 2262.88
  5107.4 2267.46  5119.2 2269.34  5189.5 2271.02  5245.1 2274.13  5345.1 2284.62
#Mann= 3 ,-1 , 0
  4549.3     .06       0  4993.6     .05       0  5011.1     .06       0
#XS Ineff= 2 , 0
       0    4951 2259.41    5049       0 2261.11
Permanent Ineff=
       F       F
Bank Sta=4993.6,5011.1
Exp/Cntr=0.5,0.3

Type RM Length L Ch R = 3 ,3396    ,,,
BEGIN DESCRIPTION:
XS 24 TOR
Structure ID: XS 24
Approximate Survey Structure
END DESCRIPTION:
Bridge Culvert--1,0,-1,-1, 0
Deck Dist Width WeirC Skew NumUp NumDn MinLoCord MaxHiCord MaxSubmerge Is_Ogee
44,10,3,0, 60, 60, , , , 0, 1,1,,
  4527.4  4543.1  4562.1  4565.1  4571.5  4578.1  4583.9  4597.7  4615.8  4623.7
  4625.8  4637.2  4653.6  4664.4    4689  4703.1  4732.8  4755.2  4780.1  4783.2
  4786.5  4794.9  4799.7    4808  4817.5  4834.8    4852  4863.8  4870.5  4889.3
  4894.5  4905.7  4911.6  4920.6  4929.7  4969.3    4995    4995    5005    5005
  5024.5  5048.2  5071.1    5083  5091.4  5103.1    5126  5150.2  5181.7  5193.7
  5209.3    5220  5246.9  5252.3  5268.7    5277  5291.6  5304.6  5316.1  5345.6
 2289.72 2283.31 2276.42 2275.76 2275.16 2273.09  2271.8 2269.27 2266.13 2265.29
 2264.86 2266.97  2267.3 2267.26  2268.1 2267.48 2266.82 2265.38 2264.72 2264.08
 2263.81 2261.51 2260.49 2260.47  2260.8 2259.99  2260.6 2260.16 2260.23 2261.16
 2260.94 2260.99  2260.4 2260.52 2259.97 2258.86 2259.33 2259.33 2259.33 2259.33
  2259.9 2261.12 2261.02 2264.53 2266.07 2266.91  2267.2 2268.11 2269.99 2271.27
 2272.55 2273.14 2275.51 2275.77 2277.57 2278.85 2280.57 2282.75 2284.23 2287.19
    2231    2231    2231    2231    2231    2231    2231    2231    2231    2231
    2231    2231    2231    2231    2231    2231    2231    2231    2231    2231
    2231    2231    2231    2231    2231    2231    2231    2231    2231    2231
    2231    2231    2231    2231    2231    2231    2231 2257.33 2257.33    2231
    2231    2231    2231    2231    2231    2231    2231    2231    2231    2231
    2231    2231    2231    2231    2231    2231    2231    2231    2231    2231
  4527.4  4543.1  4562.1  4565.1  4571.5  4578.1  4583.9  4597.7  4615.8  4623.7
  4625.8  4637.2  4653.6  4664.4    4689  4703.1  4732.8  4755.2  4780.1  4783.2
  4786.5  4794.9  4799.7    4808  4817.5  4834.8    4852  4863.8  4870.5  4889.3
  4894.5  4905.7  4911.6  4920.6  4929.7  4969.3    4995    4995    5005    5005
  5024.5  5048.2  5071.1    5083  5091.4  5103.1    5126  5150.2  5181.7  5193.7
  5209.3    5220  5246.9  5252.3  5268.7    5277  5291.6  5304.6  5316.1  5345.6
 2289.72 2283.31 2276.42 2275.76 2275.16 2273.09  2271.8 2269.27 2266.13 2265.29
 2264.86 2266.97  2267.3 2267.26  2268.1 2267.48 2266.82 2265.38 2264.72 2264.08
 2263.81 2261.51 2260.49 2260.47  2260.8 2259.99  2260.6 2260.16 2260.23 2261.16
 2260.94 2260.99  2260.4 2260.52 2259.97 2258.86 2259.33 2259.33 2259.33 2259.33
  2259.9 2261.12 2261.02 2264.53 2266.07 2266.91  2267.2 2268.11 2269.99 2271.27
 2272.55 2273.14 2275.51 2275.77 2277.57 2278.85 2280.57 2282.75 2284.23 2287.19
    2231    2231    2231    2231    2231    2231    2231    2231    2231    2231
    2231    2231    2231    2231    2231    2231    2231    2231    2231    2231
    2231    2231    2231    2231    2231    2231    2231    2231    2231    2231
    2231    2231    2231    2231    2231    2231    2231 2257.33 2257.33    2231
    2231    2231    2231    2231    2231    2231    2231    2231    2231    2231
    2231    2231    2231    2231    2231    2231    2231    2231    2231    2231
BR Coef= 1 , 1 , 0 ,1.25, 0 ,,,0.8,0,2,0,
WSPro=,,,, 1 ,,,, 0 ,,,, 0 ,,,,-1 ,-1 ,-1 , 0 , 0 , 0 , 0 , 0
BC Design=,, 0 ,, 0 ,,,,,,
BC HTab HWMax=2289.35

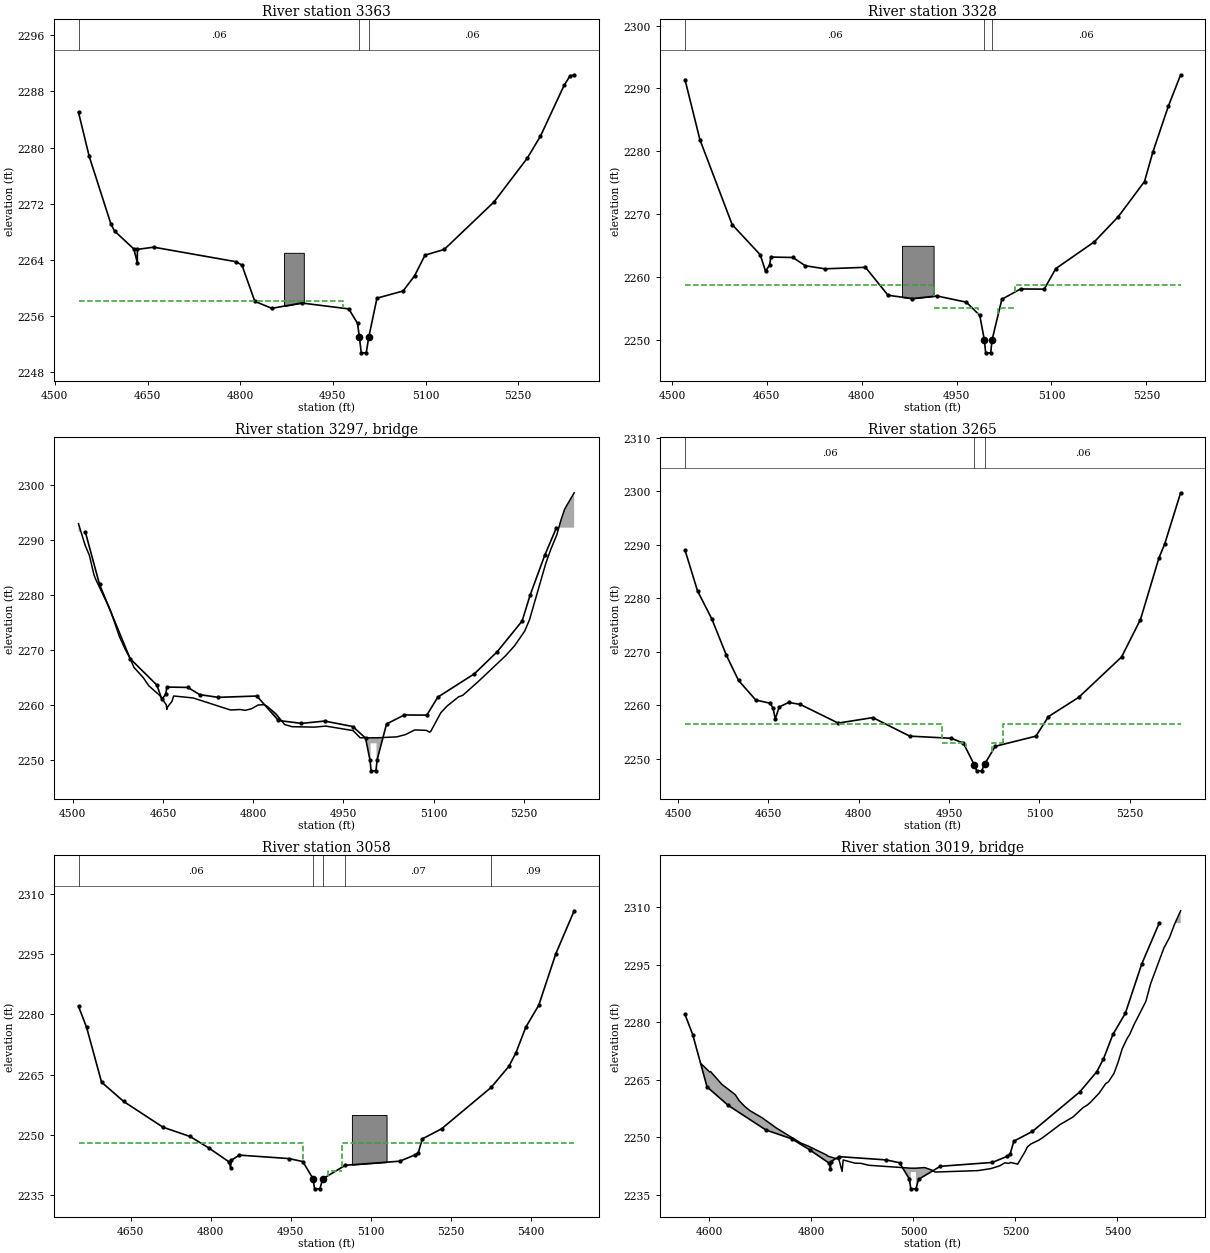
Type RM Length L Ch R = 1 ,3363    ,35,35,35
BEGIN DESCRIPTION:
XS 23
END DESCRIPTION:
XS GIS Cut Line= 6
       750521.19       627609.22       750393.38       627603.85
       750262.79       627567.87       750153.52       627562.54
       750008.27       627534.55       749729.18       627571.99
#Sta/Elev= 30
  4538.3    2285  4555.5 2278.77  4590.8 2269.09  4596.6  2268.1    4628 2265.54
  4633.5 2263.58  4633.6 2265.49  4660.1  2265.8  4793.9 2263.72  4802.9 2263.23
  4823.7 2258.08  4851.3 2257.09  4899.4 2257.85  4975.7 2257.01  4989.9 2254.96
  4992.9 2253.02    4996 2250.75    5004 2250.75  5008.1 2252.97  5021.4 2258.54
  5063.7 2259.56  5082.2 2261.71  5099.2 2264.67  5130.3 2265.48  5210.8 2272.24
  5264.8 2278.49  5286.1 2281.63  5324.3 2288.85  5333.8 2290.19  5340.6 2290.36
#Mann= 3 ,-1 , 0
  4538.3     .06       0  4992.9    .052       0  5008.1     .06       0
#XS Ineff= 3 ,-1
                          4538.3    4967  2258.2    5033  5340.6  2258.2
Permanent Ineff=
       F       F       F
#Block Obstruct= 1 ,-1
    4871    4903    2265
Bank Sta=4992.9,5008.1
Exp/Cntr=0.5,0.3

Type RM Length L Ch R = 1 ,3328    ,63,63,63
BEGIN DESCRIPTION:
XS 22
END DESCRIPTION:
XS GIS Cut Line= 6
       750550.62        627561.2       750436.02       627553.21
       750153.52       627533.22       750002.94       627491.91
       749925.65       627487.91       749773.74       627489.25
#Sta/Elev= 30
  4520.7 2291.42  4544.3 2281.87  4595.3 2268.37  4639.7 2263.58    4648 2260.98
  4654.5 2261.94  4656.4 2263.22  4691.3 2263.15  4710.9 2261.84  4741.8 2261.35
    4806 2261.59  4841.7 2257.15  4880.1 2256.62  4918.8 2257.04  4965.4 2256.05
  4986.7 2253.95    4994    2250    4996    2248    5004    2248    5006    2250
  5021.6 2256.51  5051.1 2258.15  5088.6 2258.12  5106.8 2261.38  5167.8 2265.64
  5205.6 2269.63  5247.1 2275.22  5260.2 2279.87  5284.7 2287.17  5304.2 2292.18
#Mann= 3 ,-1 , 0
  4520.7     .06       0    4994     .05       0    5006     .06       0
#XS Ineff= 4 ,-1
  4520.7  4913.7 2258.75  4913.9    4984  2255.2    5016    5042  2255.2
  5042.5  5304.2 2258.75
Permanent Ineff=
       F       F       F       F
#Block Obstruct= 1 ,-1
  4863.7  4913.7    2265
Bank Sta=4994,5006
Exp/Cntr=0.5,0.3

Type RM Length L Ch R = 3 ,3297    ,,,
BEGIN DESCRIPTION:
XS 21 TOR
Structure ID: XS 21
Approximate Survey Structure
END DESCRIPTION:
Bridge Culvert--1,0,-1,-1, 0
Deck Dist Width WeirC Skew NumUp NumDn MinLoCord MaxHiCord MaxSubmerge Is_Ogee
27.5,7,3,0, 60, 60, , , , 0, 1,1,,
  4509.4  4520.3  4527.5  4535.1  4537.6  4559.5  4563.8  4577.4  4586.8    4596
  4601.3  4617.2  4626.3  4644.8  4655.3  4656.2  4656.9    4659  4664.6  4667.6
    4700  4762.1  4778.1  4786.5  4797.3  4807.8  4817.6  4822.5  4837.6  4852.1
  4864.2  4901.7  4920.6    4966  4977.9    4995    4995    5005    5005  5038.6
  5053.2  5068.5    5088  5093.1  5095.4    5112  5122.8  5141.4  5148.4  5174.6
  5219.7  5234.5  5251.5  5259.5  5286.8    5295  5304.8  5311.7  5317.7  5333.6
 2292.89 2289.01 2287.13 2283.61 2282.88 2277.86 2276.72 2272.39 2270.14 2268.26
 2266.83 2264.91 2263.45 2261.66 2260.01 2259.16 2259.46 2259.82 2260.58  2261.6
 2261.24 2259.05 2259.14 2258.99 2259.29 2259.95 2260.02 2259.77 2258.36 2256.42
 2256.02 2255.94 2256.13 2255.31    2254    2254    2254    2254    2254 2254.17
 2254.59 2255.43 2255.35 2255.02 2255.22 2258.58 2259.82 2261.44 2261.72 2264.27
 2268.92 2270.72 2273.41 2275.51 2285.82 2288.31  2290.9 2293.57 2295.53 2298.51
    2228    2228    2228    2228    2228    2228    2228    2228    2228    2228
    2228    2228    2228    2228    2228    2228    2228    2228    2228    2228
    2228    2228    2228    2228    2228    2228    2228    2228    2228    2228
    2228    2228    2228    2228    2228    2228    2253    2253    2228    2228
    2228    2228    2228    2228    2228    2228    2228    2228    2228    2228
    2228    2228    2228    2228    2228    2228    2228    2228    2228    2228
  4509.4  4520.3  4527.5  4535.1  4537.6  4559.5  4563.8  4577.4  4586.8    4596
  4601.3  4617.2  4626.3  4644.8  4655.3  4656.2  4656.9    4659  4664.6  4667.6
    4700  4762.1  4778.1  4786.5  4797.3  4807.8  4817.6  4822.5  4837.6  4852.1
  4864.2  4901.7  4920.6    4966  4977.9    4995    4995    5005    5005  5038.6
  5053.2  5068.5    5088  5093.1  5095.4    5112  5122.8  5141.4  5148.4  5174.6
  5219.7  5234.5  5251.5  5259.5  5286.8    5295  5304.8  5311.7  5317.7  5333.6
 2292.89 2289.01 2287.13 2283.61 2282.88 2277.86 2276.72 2272.39 2270.14 2268.26
 2266.83 2264.91 2263.45 2261.66 2260.01 2259.16 2259.46 2259.82 2260.58  2261.6
 2261.24 2259.05 2259.14 2258.99 2259.29 2259.95 2260.02 2259.77 2258.36 2256.42
 2256.02 2255.94 2256.13 2255.31    2254    2254    2254    2254    2254 2254.17
 2254.59 2255.43 2255.35 2255.02 2255.22 2258.58 2259.82 2261.44 2261.72 2264.27
 2268.92 2270.72 2273.41 2275.51 2285.82 2288.31  2290.9 2293.57 2295.53 2298.51
    2228    2228    2228    2228    2228    2228    2228    2228    2228    2228
    2228    2228    2228    2228    2228    2228    2228    2228    2228    2228
    2228    2228    2228    2228    2228    2228    2228    2228    2228    2228
    2228    2228    2228    2228    2228    2228    2253    2253    2228    2228
    2228    2228    2228    2228    2228    2228    2228    2228    2228    2228
    2228    2228    2228    2228    2228    2228    2228    2228    2228    2228
BR Coef= 1 , 1 , 0 ,1.25, 0 ,,,0.8,0,2,0,
WSPro=,,,, 1 ,,,, 0 ,,,, 0 ,,,,-1 ,-1 ,-1 , 0 , 0 , 0 , 0 , 0
BC Design=,, 0 ,, 0 ,,,,,,
BC HTab HWMax=2292.18

Type RM Length L Ch R = 1 ,3265    ,207,207,207
BEGIN DESCRIPTION:
XS 20
END DESCRIPTION:
XS GIS Cut Line= 6
       750563.95       627513.23       750440.02       627499.91
       750278.78       627479.92        750162.9       627477.65
       750022.93       627429.28       749751.09       627417.29
#Sta/Elev= 30
  4511.3 2289.02  4532.1 2281.38    4556 2276.11  4580.2 2269.31  4600.2 2264.65
  4628.9 2260.98  4652.9 2260.38  4657.6 2259.43  4661.3 2257.45  4667.8 2259.69
  4683.5 2260.53  4702.8 2260.16  4765.8 2256.67  4823.3  2257.7  4884.7 2254.23
  4953.1 2253.84  4973.6 2252.95  4991.7 2248.89    4996 2247.75    5004 2247.75
  5009.5 2249.12  5026.7 2252.34  5094.1 2254.23    5115 2257.89  5165.1 2261.47
  5236.4 2269.03  5267.8 2276.03  5298.4  2287.5    5308 2290.13  5334.5 2299.71
#Mann= 3 ,-1 , 0
  4511.3     .06       0  4991.7     .05       0  5009.5     .06       0
#XS Ineff= 4 ,-1
  4511.3  4938.6 2256.52    4939  4977.3    2253 5021.45    5040    2253
  5040.1  5334.5 2256.52
Permanent Ineff=
       F       F       F       F
Bank Sta=4991.7,5009.5
Exp/Cntr=0.5,0.3

Type RM Length L Ch R = 1 ,3058    ,76,76,76
BEGIN DESCRIPTION:
XS 19
END DESCRIPTION:
XS GIS Cut Line= 6
       750539.23       627096.63       750481.79       627178.41
       750390.43       627260.79       750315.54       627284.76
       749974.03       627245.81       749701.37       627325.52
#Sta/Elev= 30
  4552.3 2282.03  4567.5 2276.77  4595.5 2263.17  4636.9 2258.36  4710.9 2251.94
  4761.4 2249.65  4796.5  2246.8  4835.1 2243.28  4837.4 2241.87  4838.7 2243.72
  4853.9 2245.01  4946.9 2244.15  4972.8 2243.41  4992.1 2239.17    4995 2236.62
    5005 2236.62  5010.3 2239.11  5052.8 2242.49  5154.9  2243.5  5184.2 2245.11
  5189.5 2245.61  5196.9 2249.04  5233.1 2251.55    5326 2261.84  5359.3 2267.09
  5372.5 2270.43    5391 2276.81  5415.4 2282.31  5447.5 2295.15  5481.8  2305.8
#Mann= 5 ,-1 , 0
  4552.3     .06       0  4992.1     .05       0  5010.3     .06       0
  5052.8     .07       0    5326     .09       0
#XS Ineff= 4 ,-1
  4552.3 4972.82    2248 4972.85 4982.01    2241  5020.3  5046.4    2241
  5046.5  5481.8    2248
Permanent Ineff=
       F       F       F       F
#Block Obstruct= 1 ,-1
    5065    5130    2255
Bank Sta=4992.1,5010.3
Exp/Cntr=0.5,0.3

Type RM Length L Ch R = 3 ,3019    ,,,
BEGIN DESCRIPTION:
XS 18 TOR
Structure ID: XS 18
Approximate Survey Structure
END DESCRIPTION:
Bridge Culvert--1,0,-1,-1, 0
Deck Dist Width WeirC Skew NumUp NumDn MinLoCord MaxHiCord MaxSubmerge Is_Ogee
31.5,15,3,0, 60, 60, , , , 0, 1,1,,
  4584.5  4600.7  4602.5  4624.8  4650.8  4658.6  4669.5  4679.8  4703.8  4731.5
  4779.5    4794    4830  4831.8    4853  4854.1  4860.3  4862.4  4885.7    4897
  4912.3    4995    4995    5005    5005  5022.1  5036.2  5042.8  5126.6  5151.6
  5168.8  5179.4  5186.8  5190.6  5204.4  5219.3  5223.4  5230.2  5245.6  5254.9
  5287.4    5313  5332.7  5340.9  5347.3    5364    5377  5382.4  5393.2  5401.1
  5409.4    5419  5423.7  5432.8  5455.6  5464.9  5490.9  5501.9  5512.1  5523.8
  2269.1 2267.06 2267.14  2263.8 2261.15 2259.56 2258.07 2256.96  2255.1 2252.45
 2248.53 2247.75 2245.42 2245.16 2244.32 2244.22 2241.15 2244.14  2243.3 2243.26
 2242.76    2242    2242    2242    2242 2242.16  2241.5 2240.99 2241.37 2241.88
 2242.59  2243.4 2243.24 2243.49 2243.05  2246.4 2247.53  2248.3 2249.27 2250.09
 2253.35 2255.34 2257.79 2258.43 2259.19 2261.53 2264.02  2264.5 2266.69 2269.54
 2273.13 2275.79 2276.76 2279.47 2285.41    2290  2299.3 2302.04 2305.59 2309.02
  2215.5  2215.5  2215.5  2215.5  2215.5  2215.5  2215.5  2215.5  2215.5  2215.5
  2215.5  2215.5  2215.5  2215.5  2215.5  2215.5  2215.5  2215.5  2215.5  2215.5
  2215.5  2215.5    2241    2241  2215.5  2215.5  2215.5  2215.5  2215.5  2215.5
  2215.5  2215.5  2215.5  2215.5  2215.5  2215.5  2215.5  2215.5  2215.5  2215.5
  2215.5  2215.5  2215.5  2215.5  2215.5  2215.5  2215.5  2215.5  2215.5  2215.5
  2215.5  2215.5  2215.5  2215.5  2215.5  2215.5  2215.5  2215.5  2215.5  2215.5
  4584.5  4600.7  4602.5  4624.8  4650.8  4658.6  4669.5  4679.8  4703.8  4731.5
  4779.5    4794    4830  4831.8    4853  4854.1  4860.3  4862.4  4885.7    4897
  4912.3    4995    4995    5005    5005  5022.1  5036.2  5042.8  5126.6  5151.6
  5168.8  5179.4  5186.8  5190.6  5204.4  5219.3  5223.4  5230.2  5245.6  5254.9
  5287.4    5313  5332.7  5340.9  5347.3    5364    5377  5382.4  5393.2  5401.1
  5409.4    5419  5423.7  5432.8  5455.6  5464.9  5490.9  5501.9  5512.1  5523.8
  2269.1 2267.06 2267.14  2263.8 2261.15 2259.56 2258.07 2256.96  2255.1 2252.45
 2248.53 2247.75 2245.42 2245.16 2244.32 2244.22 2241.15 2244.14  2243.3 2243.26
 2242.76    2242    2242    2242    2242 2242.16  2241.5 2240.99 2241.37 2241.88
 2242.59  2243.4 2243.24 2243.49 2243.05  2246.4 2247.53  2248.3 2249.27 2250.09
 2253.35 2255.34 2257.79 2258.43 2259.19 2261.53 2264.02  2264.5 2266.69 2269.54
 2273.13 2275.79 2276.76 2279.47 2285.41    2290  2299.3 2302.04 2305.59 2309.02
  2215.5  2215.5  2215.5  2215.5  2215.5  2215.5  2215.5  2215.5  2215.5  2215.5
  2215.5  2215.5  2215.5  2215.5  2215.5  2215.5  2215.5  2215.5  2215.5  2215.5
  2215.5  2215.5    2241    2241  2215.5  2215.5  2215.5  2215.5  2215.5  2215.5
  2215.5  2215.5  2215.5  2215.5  2215.5  2215.5  2215.5  2215.5  2215.5  2215.5
  2215.5  2215.5  2215.5  2215.5  2215.5  2215.5  2215.5  2215.5  2215.5  2215.5
  2215.5  2215.5  2215.5  2215.5  2215.5  2215.5  2215.5  2215.5  2215.5  2215.5
BR Coef= 1 , 1 , 0 ,1.25, 0 ,,,0.8,0,2,0,
WSPro=,,,, 1 ,,,, 0 ,,,, 0 ,,,,-1 ,-1 ,-1 , 0 , 0 , 0 , 0 , 0
BC Design=,, 0 ,, 0 ,,,,,,
BC HTab HWMax=2305.8

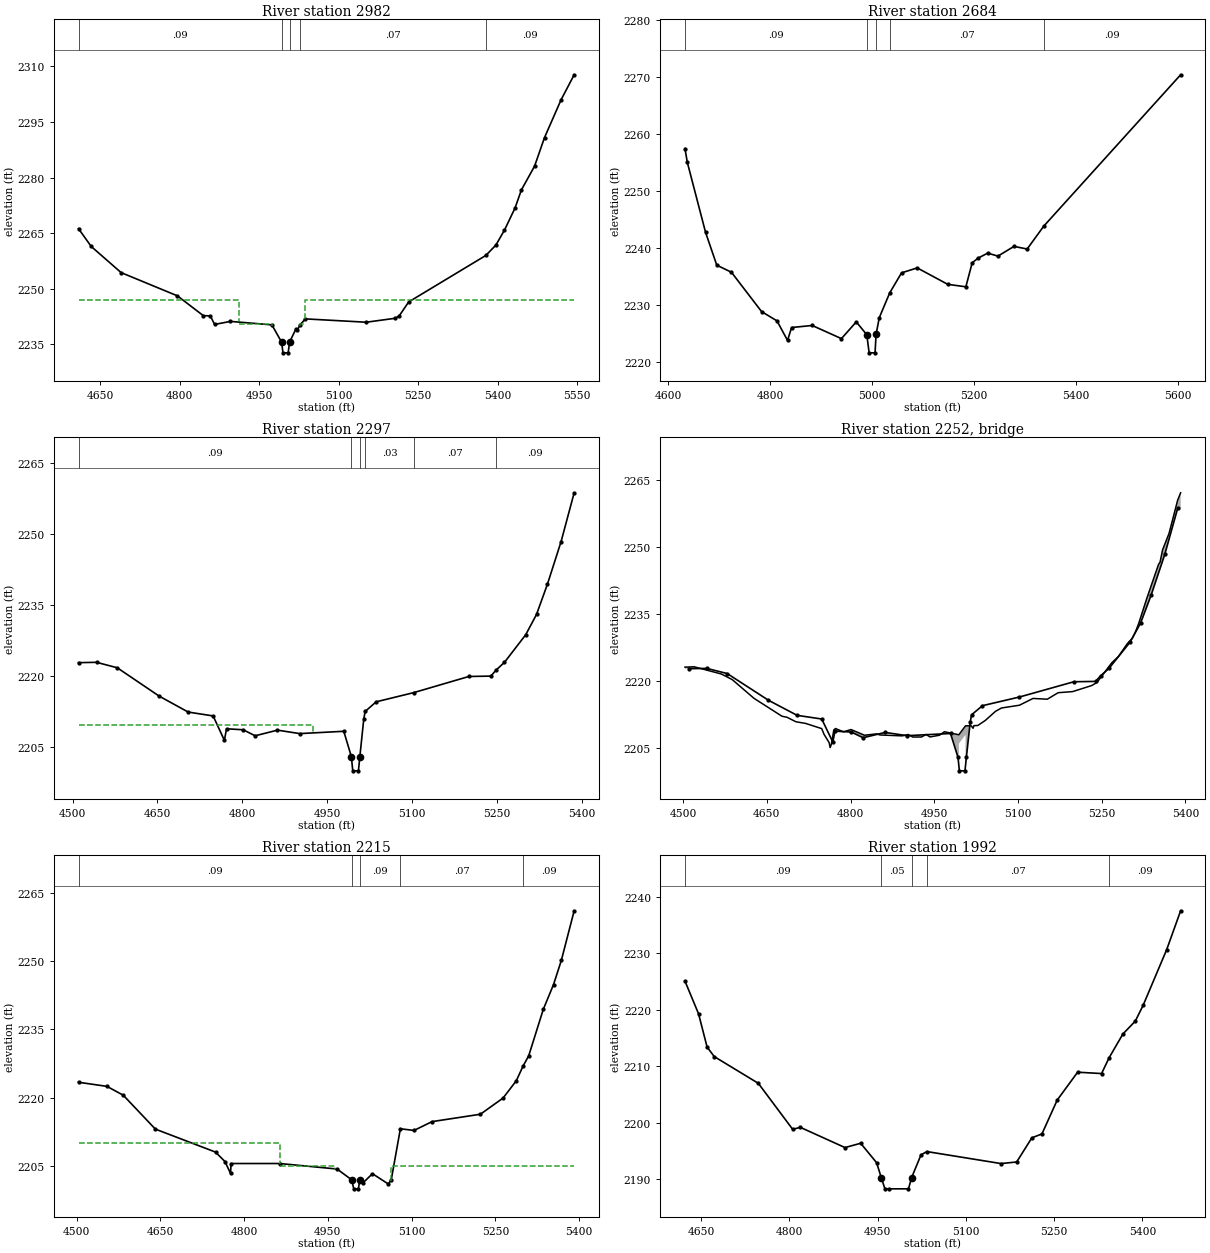
Type RM Length L Ch R = 1 ,2982    ,298,298,298
BEGIN DESCRIPTION:
XS 17
END DESCRIPTION:
XS GIS Cut Line= 6
        750500.4       627035.33        750411.4       627157.44
       750321.53       627212.86       750120.82       627188.89
       749981.52       627166.43       749662.54        627268.3
#Sta/Elev= 30
  4609.4 2266.24  4633.4 2261.43  4689.7 2254.39    4796 2248.11  4844.8 2242.77
  4857.9 2242.71  4866.1  2240.4  4895.9 2241.22  4974.1 2240.29  4992.5 2235.61
    4995 2232.74  5004.8 2232.74  5007.5 2235.64  5019.5  2239.2    5022 2238.84
  5027.3 2240.29  5037.3  2241.9  5152.1    2241    5206 2242.05  5213.8 2242.62
  5232.1 2246.47  5377.7 2259.02  5396.6 2261.82  5412.8 2265.85  5432.8 2271.85
  5444.7  2276.7  5469.5 2283.09  5488.3 2290.82  5519.7 2301.06  5544.2 2307.75
#Mann= 5 ,-1 , 0
  4609.4     .09       0  4992.5     .05       0  5007.5     .09       0
  5027.3     .07       0  5377.7     .09       0
#XS Ineff= 4 ,-1
  4609.4  4912.7    2247  5026.5  5037.3  2240.5  5037.3  5544.2    2247
  4912.7    4975  2240.5
Permanent Ineff=
       F       F       F       F
Bank Sta=4992.5,5007.5
Exp/Cntr=0.5,0.3

Type RM Length L Ch R = 1 ,2684    ,387,387,387
BEGIN DESCRIPTION:
XS 16
END DESCRIPTION:
XS GIS Cut Line= 6
       750524.93       626908.63       750314.44       626875.93
       750189.78       626896.36       750099.86       626931.11
       749864.85       626943.37       749576.71       627027.15
#Sta/Elev= 30
  4633.4 2257.45    4638 2255.03  4673.7 2242.74  4695.7 2236.96  4724.4 2235.72
  4783.5  2228.8  4813.7 2227.17  4834.3 2223.73  4842.3    2226  4882.6 2226.36
  4939.9 2224.05    4969 2226.99  4989.6 2224.74  4994.2 2221.55  5005.8 2221.55
  5007.8 2224.78    5014 2227.71  5034.6  2232.1  5057.7 2235.61  5088.4 2236.48
  5148.3 2233.59  5183.7 2233.16  5196.1 2237.37  5207.6  2238.2  5226.6 2239.08
  5246.5 2238.55    5278 2240.26  5303.8  2239.8  5336.5 2243.84  5604.5 2270.43
#Mann= 5 ,-1 , 0
  4633.4     .09       0  4989.6     .05       0  5007.8     .09       0
  5034.6     .07       0  5336.5     .09       0
Bank Sta=4989.6,5007.8
Exp/Cntr=0.5,0.3

Type RM Length L Ch R = 1 ,2297    ,82,82,82
BEGIN DESCRIPTION:
XS 15
END DESCRIPTION:
XS GIS Cut Line= 5
       750514.71       626483.56       750329.68       626535.39
       750099.93       626546.33       749917.06       626546.33
       749650.28       626591.87
#Sta/Elev= 30
  4510.5 2222.84  4542.3 2222.91  4578.9 2221.76  4652.9 2215.78  4704.2 2212.41
  4748.3 2211.59  4768.2 2206.44    4772 2208.88  4801.3 2208.67  4822.5  2207.4
    4862 2208.59  4901.3 2207.86  4979.1 2208.35  4992.5 2203.01    4995    2200
    5005    2200  5007.5 2203.01  5014.4 2210.91  5016.8 2212.53  5036.3 2214.57
  5102.6 2216.51  5200.1 2219.92  5238.9    2220    5248 2221.25    5263 2222.91
  5300.5 2228.73  5319.6 2233.02  5338.8 2239.38    5363  2248.4  5386.1  2258.7
#Mann= 6 ,-1 , 0
  4510.5     .09       0  4992.5     .05       0  5007.5     .09       0
  5016.8     .03       0  5102.6     .07       0    5248     .09       0
#XS Ineff= 2 , 0
       0    4925 2209.64  5046.5       0  2211.8
Permanent Ineff=
       F       F
Bank Sta=4992.5,5007.5
Exp/Cntr=0.5,0.3

Type RM Length L Ch R = 3 ,2252    ,,,
BEGIN DESCRIPTION:
XS 14 TOR
Structure ID: XS 14 tor
Approximate Survey Structure
END DESCRIPTION:
Bridge Culvert--1,0,-1,-1, 0
Deck Dist Width WeirC Skew NumUp NumDn MinLoCord MaxHiCord MaxSubmerge Is_Ogee
40.5,9,3,0, 60, 60, , , , 0, 1,1,,
  4503.3  4519.7  4568.6    4588    4627  4677.1    4686  4701.9  4719.3  4748.3
  4752.5  4761.5  4763.4  4765.5    4770    4773  4787.3  4800.7    4825  4846.8
  4852.7  4892.4  4903.3  4911.3  4927.1  4935.3  4942.3  4959.2  4968.1    4994
    4994    5006    5006  5016.1  5019.5    5021    5028  5041.4  5059.7  5070.6
  5102.5  5126.9  5152.5  5171.9    5198  5231.8  5241.4    5268  5279.8    5296
  5304.9  5310.5    5316  5331.2  5351.9  5354.5  5359.1  5370.6  5386.1  5391.4
 2223.19 2223.27 2221.65  2220.4 2216.21 2212.21 2211.99 2210.98 2210.61 2209.44
 2208.16 2206.33  2205.2 2205.89 2209.15 2209.46 2208.72 2209.24 2207.96 2208.27
 2208.02 2207.82 2208.13 2207.56 2207.57 2208.14 2207.58 2207.96 2208.74 2208.07
 2208.07 2210.07 2210.07 2210.08 2209.52 2210.11 2210.14 2211.27 2213.31 2214.06
 2214.67 2216.19 2216.02 2217.47 2217.72 2219.06 2219.75 2224.16 2225.55 2228.47
 2229.65  2231.1 2232.87 2238.73  2246.2 2246.66 2249.44 2253.09 2260.55 2262.18
    2179    2179    2179    2179    2179    2179    2179    2179    2179    2179
    2179    2179    2179    2179    2179    2179    2179    2179    2179    2179
    2179    2179    2179    2179    2179    2179    2179    2179    2179    2179
 2206.08 2208.08    2179    2179    2179    2179    2179    2179    2179    2179
    2179    2179    2179    2179    2179    2179    2179    2179    2179    2179
    2179    2179    2179    2179    2179    2179    2179    2179    2179    2179
  4503.3  4519.7  4568.6    4588    4627  4677.1    4686  4701.9  4719.3  4748.3
  4752.5  4761.5  4763.4  4765.5    4770    4773  4787.3  4800.7    4825  4846.8
  4852.7  4892.4  4903.3  4911.3  4927.1  4935.3  4942.3  4959.2  4968.1    4994
    4994    5006    5006  5016.1  5019.5    5021    5028  5041.4  5059.7  5070.6
  5102.5  5126.9  5152.5  5171.9    5198  5231.8  5241.4    5268  5279.8    5296
  5304.9  5310.5    5316  5331.2  5351.9  5354.5  5359.1  5370.6  5386.1  5391.4
 2223.19 2223.27 2221.65  2220.4 2216.21 2212.21 2211.99 2210.98 2210.61 2209.44
 2208.16 2206.33  2205.2 2205.89 2209.15 2209.46 2208.72 2209.24 2207.96 2208.27
 2208.02 2207.82 2208.13 2207.56 2207.57 2208.14 2207.58 2207.96 2208.74 2208.07
 2208.07 2210.07 2210.07 2210.08 2209.52 2210.11 2210.14 2211.27 2213.31 2214.06
 2214.67 2216.19 2216.02 2217.47 2217.72 2219.06 2219.75 2224.16 2225.55 2228.47
 2229.65  2231.1 2232.87 2238.73  2246.2 2246.66 2249.44 2253.09 2260.55 2262.18
    2179    2179    2179    2179    2179    2179    2179    2179    2179    2179
    2179    2179    2179    2179    2179    2179    2179    2179    2179    2179
    2179    2179    2179    2179    2179    2179    2179    2179    2179    2179
 2206.08 2208.08    2179    2179    2179    2179    2179    2179    2179    2179
    2179    2179    2179    2179    2179    2179    2179    2179    2179    2179
    2179    2179    2179    2179    2179    2179    2179    2179    2179    2179
BR Coef= 1 , 1 , 0 ,1.25, 0 ,,,0.8,0,2,0,
WSPro=,,,, 1 ,,,, 0 ,,,, 0 ,,,,-1 ,-1 ,-1 , 0 , 0 , 0 , 0 , 0
BC Design=,, 0 ,, 0 ,,,,,,
BC HTab HWMax=2258.7

Type RM Length L Ch R = 1 ,2215    ,223,223,223
BEGIN DESCRIPTION:
XS 13
END DESCRIPTION:
XS GIS Cut Line= 6
       750508.58       626422.26        750295.3       626461.93
       750131.19       626472.87       749951.45       626463.49
        749801.5       626493.78       749629.84        626518.3
#Sta/Elev= 30
  4503.4  2223.4  4554.3  2222.5  4583.6 2220.55  4641.1 2213.11  4748.8 2208.07
  4765.8 2205.98  4775.7 2203.38  4776.7 2205.56  4863.8 2205.56  4966.5 2204.35
  4992.5    2202  4996.5    2200  5004.6    2200  5007.5    2202  5012.2 2201.22
  5029.9 2203.32  5058.1 2201.08  5063.5 2201.93  5079.9 2213.19  5104.3 2212.82
  5136.7 2214.76  5223.3 2216.38  5263.9 2219.94  5287.5 2223.72  5299.5 2226.91
  5309.8 2229.22  5335.9 2239.41  5354.2 2244.84  5368.2 2250.15  5391.2 2261.05
#Mann= 5 ,-1 , 0
  4503.4     .09       0  4992.5     .05       0  5007.5     .09       0
  5079.9     .07       0  5299.5     .09       0
#XS Ineff= 3 ,-1
  4503.4  4863.8    2210    4864  4962.8    2205 5062.86  5391.2    2205
Permanent Ineff=
       F       F       F
Bank Sta=4992.5,5007.5
Exp/Cntr=0.5,0.3

Type RM Length L Ch R = 1 ,1992    ,289,289,289
BEGIN DESCRIPTION:
XS 12
END DESCRIPTION:
XS GIS Cut Line= 6
       750416.62       626181.11       750287.87       626244.46
       750097.82        626250.6        749960.9       626244.46
       749742.24       626258.77        749595.1       626299.64
#Sta/Elev= 30
  4622.4 2225.07  4645.5 2219.28    4660  2213.4  4672.2 2211.72  4747.1 2206.99
  4805.5 2198.85  4818.4 2199.21  4894.4 2195.63    4921 2196.39  4948.1 2192.96
  4956.1  2190.3  4962.2 2188.35  4969.8 2188.33  5002.3 2188.33  5007.7 2190.33
  5023.6 2194.34  5033.6 2194.92  5159.6  2192.8  5186.2 2193.08    5212 2197.35
  5229.2 2198.05  5255.1 2204.03  5289.8 2208.96  5330.5 2208.72  5343.5 2211.55
  5366.8 2215.72  5387.9    2218  5401.2  2220.8  5441.2 2230.64  5464.9 2237.51
#Mann= 5 ,-1 , 0
  4622.4     .09       0  4956.1     .05       0  5007.7     .09       0
  5033.6     .07       0  5343.5     .09       0
Bank Sta=4956.1,5007.7
Exp/Cntr=0.3,0.1