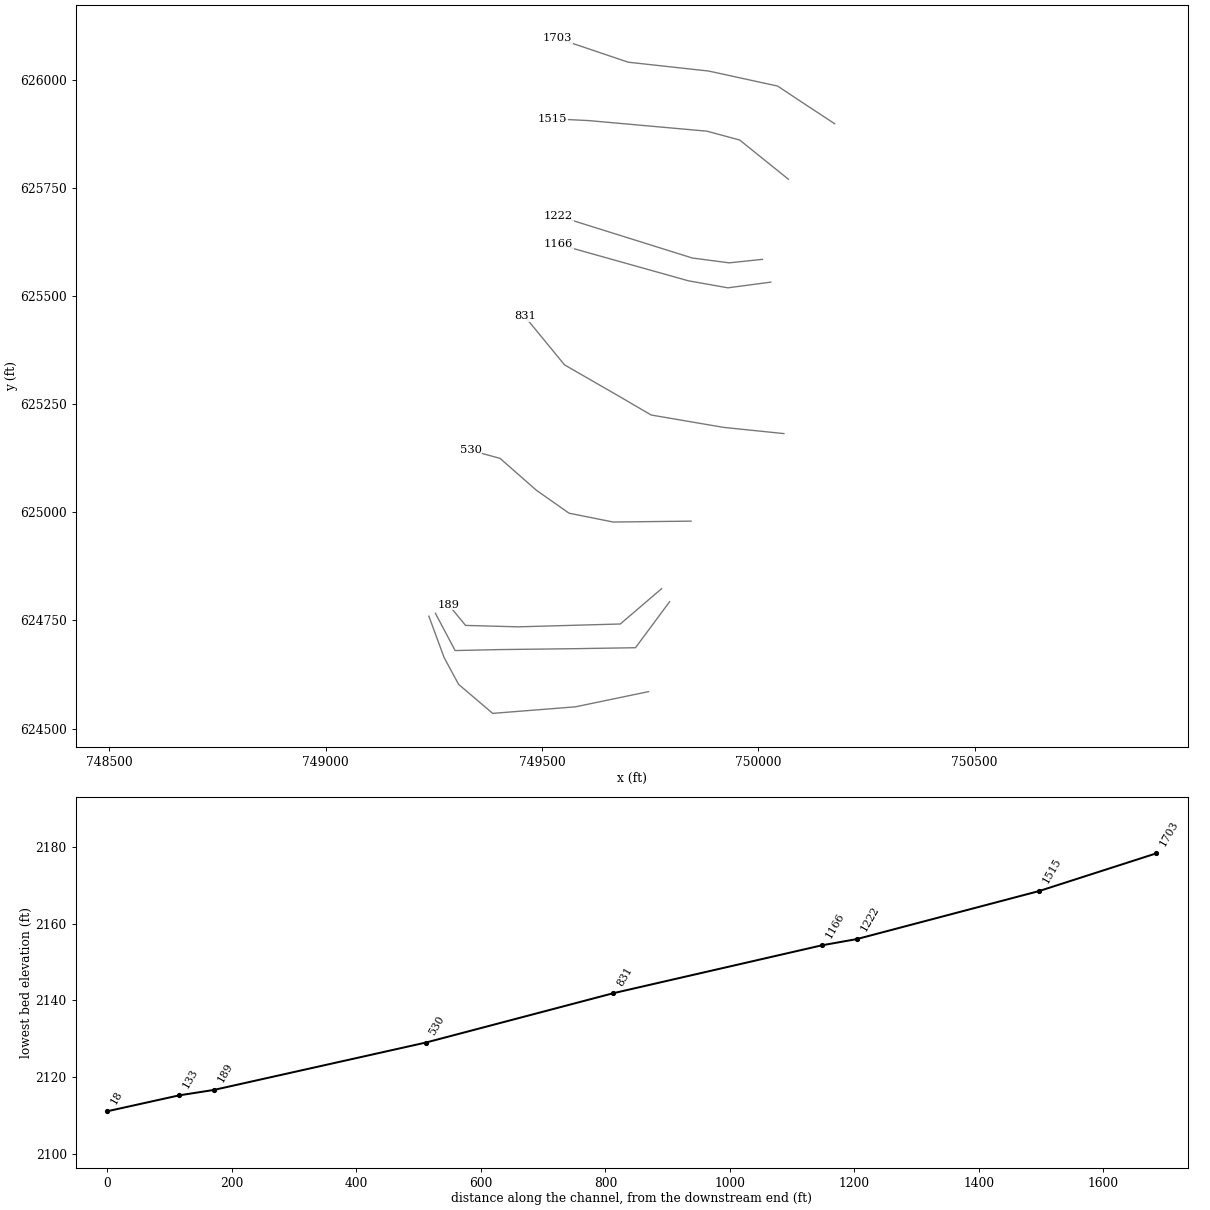
HEC-RAS study lds_fisher_crk.prj: Fisher Creek Limited Detail Study

--- lds_fisher_crk.g01 (geometry) --- (continued)

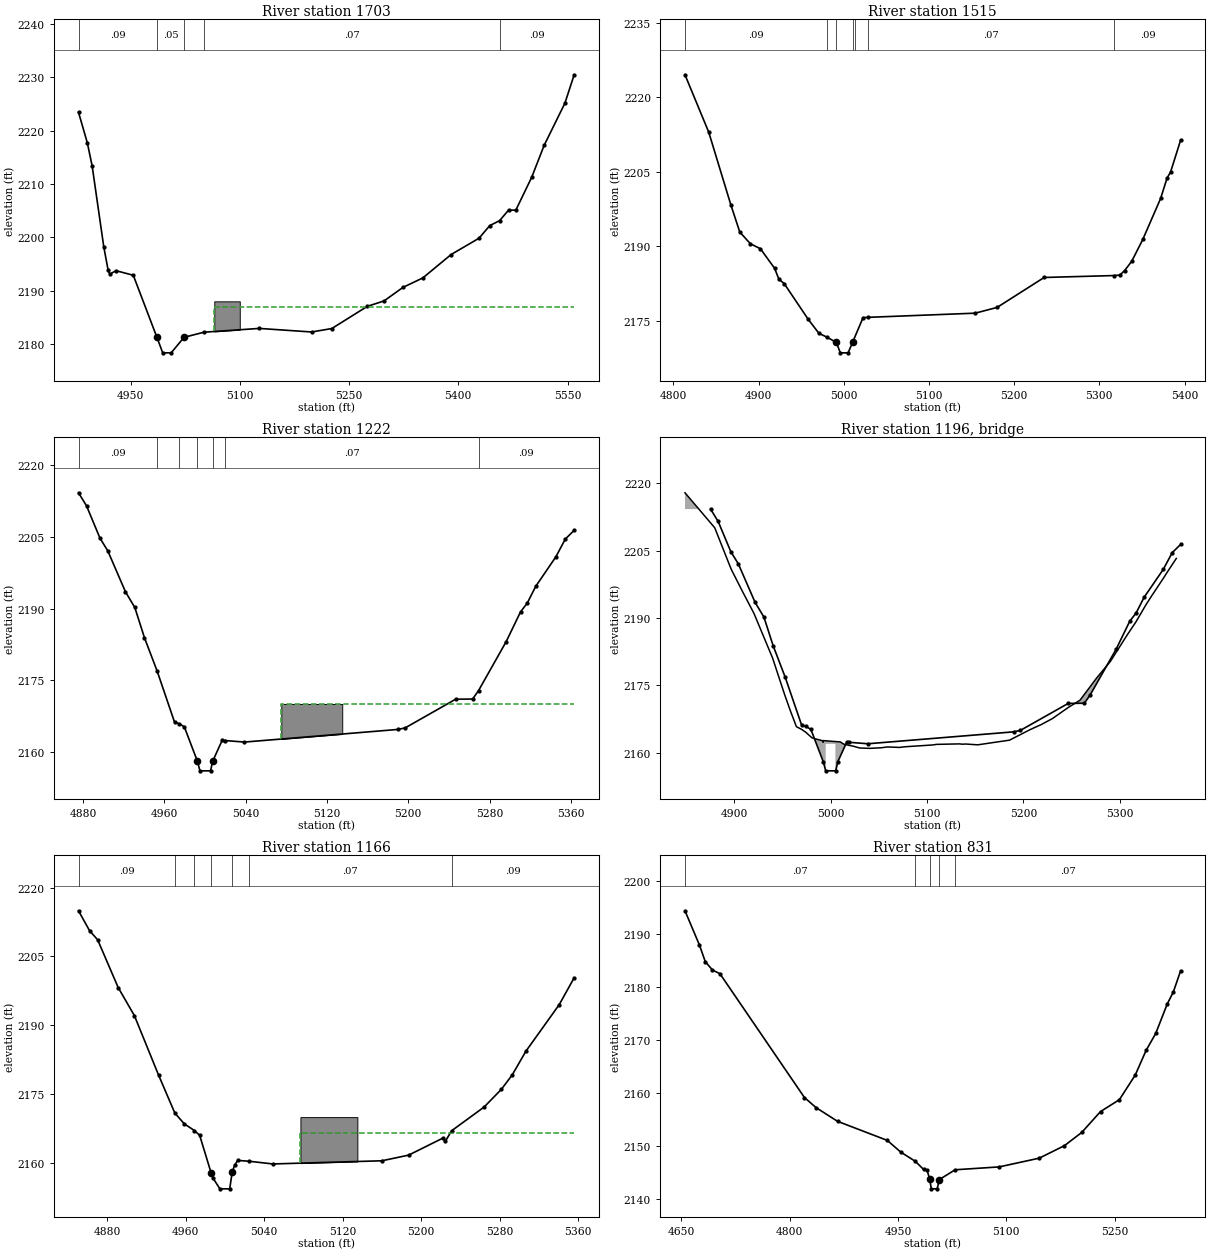
Type RM Length L Ch R = 1 ,1703    ,188,188,188
BEGIN DESCRIPTION:
XS 11
END DESCRIPTION:
XS GIS Cut Line= 6
       750176.33        625897.9       750093.73       625952.23
       750044.69       625984.93       749885.29       626019.67
       749699.32       626040.11       749535.84       626095.28
#Sta/Elev= 30
  4878.6 2223.45  4890.7 2217.73  4897.3 2213.41  4913.3  2198.2  4919.2  2193.9
  4921.5 2193.08    4930 2193.75  4953.8 2192.89    4986 2181.34  4994.2 2178.34
  5005.8 2178.34  5023.5 2181.25  5050.8 2182.21  5126.7 2182.92  5198.7 2182.25
  5226.4  2182.9  5275.1 2187.06    5298 2188.07    5324 2190.61  5351.3 2192.39
  5390.2 2196.78  5428.4 2199.83  5443.3 2202.21  5456.7 2203.13    5469  2205.1
    5479  2205.1  5500.9  2211.3  5517.8 2217.23  5546.4 2225.17  5559.1 2230.49
#Mann= 5 ,-1 , 0
  4878.6     .09       0    4986     .05       0  5023.5     .09       0
  5050.8     .07       0  5456.7     .09       0
#XS Ineff= 2 , 0
       0                    5065       0    2187
Permanent Ineff=
       F       F
#Block Obstruct= 1 ,-1
    5065    5100    2188
Bank Sta=4986,5023.5
Exp/Cntr=0.3,0.1

Type RM Length L Ch R = 1 ,1515    ,293,293,293
BEGIN DESCRIPTION:
XS 10
END DESCRIPTION:
XS GIS Cut Line= 5
       750069.45       625769.65       749956.81       625860.27
        749881.2       625880.71       749607.36       625905.23
       749523.58       625909.32
#Sta/Elev= 30
  4813.7 2224.54  4841.6 2212.97  4867.6  2198.3    4878 2192.87  4890.4 2190.51
  4902.2  2189.5  4918.8 2185.58    4924 2183.34  4930.1 2182.49  4958.3 2175.29
    4971 2172.44    4980 2171.72  4991.4 2170.62    4996 2168.53  5005.2 2168.53
 5010.49 2170.69  5022.7 2175.62  5028.5 2175.68  5154.3 2176.52    5180 2177.68
  5235.2 2183.71  5317.6  2184.1  5324.1  2184.2  5329.6 2185.09    5338 2186.97
  5351.1 2191.41  5371.9 2199.62  5379.5 2203.74  5383.6 2204.96  5395.4 2211.38
#Mann= 7 ,-1 , 0
  4813.7     .09       0    4980     .05       0  4991.4     .05       0
 5010.49     .05       0  5012.9     .09       0  5028.5     .07       0
  5317.6     .09       0
Bank Sta=4991.4,5010.49
Exp/Cntr=0.5,0.3

Type RM Length L Ch R = 1 ,1222    ,56,56,56
BEGIN DESCRIPTION:
XS 9
END DESCRIPTION:
XS GIS Cut Line= 4
       750009.54       625584.52       749932.59       625576.42
       749847.54       625587.55       749537.88       625684.53
#Sta/Elev= 30
  4875.5 2214.27  4883.4 2211.53  4896.6 2204.77  4904.3  2202.1  4921.7 2193.52
  4930.9 2190.23  4940.4 2183.89  4952.9 2176.89    4970 2166.19  4974.5 2165.88
  4979.6 2165.23  4992.5    2158    4995    2156  5005.4    2156  5007.5    2158
  5016.9 2162.43  5019.5 2162.35  5038.8 2162.03    5190 2164.68    5197 2165.01
  5246.6 2171.01  5263.3 2171.05  5269.1 2172.81  5296.3 2183.08  5310.4  2189.3
  5317.1 2191.17  5325.3 2194.63  5345.2 2200.85  5354.5 2204.58  5363.2  2206.4
#Mann= 7 ,-1 , 0
  4875.5     .09       0  4952.9     .07       0  4974.5     .09       0
  4992.5     .05       0  5007.5     .09       0  5019.5     .07       0
  5269.1     .09       0
#XS Ineff= 2 , 0
       0    4975 2164.46    5075       0    2170
Permanent Ineff=
       F       F
#Block Obstruct= 1 ,-1
    5075    5135    2170
Bank Sta=4992.5,5007.5
Exp/Cntr=0.5,0.3

Type RM Length L Ch R = 3 ,1196    ,,,
BEGIN DESCRIPTION:
XS 8 TOR
Structure ID: XS 8
Approximate Survey Structure
END DESCRIPTION:
Bridge Culvert--1,0,-1,-1, 0
Deck Dist Width WeirC Skew NumUp NumDn MinLoCord MaxHiCord MaxSubmerge Is_Ogee
20,12,3,0, 60, 60, , , , 0, 1,1,,
    4849  4879.8  4880.1  4895.6  4897.3  4908.9  4920.6  4939.9  4952.4  4958.4
  4964.6  4969.9  4974.2  4980.7    4984  4991.5  4992.4  4992.5    4995    4995
    5005    5005  5010.1  5013.6  5014.5  5022.4  5023.1  5030.1  5040.5  5041.6
  5042.4  5052.7  5059.2  5071.5  5076.6  5105.9  5109.8  5133.8  5136.7  5140.1
  5152.7  5185.7    5208  5208.6  5210.3  5218.6  5230.3  5246.7  5258.8    5276
  5290.1  5290.3  5290.6    5308  5316.7  5326.9  5331.7  5346.8  5347.6  5358.7
  2217.9 2210.13 2209.99  2201.6 2200.73 2195.83 2191.03  2181.1 2172.96 2169.33
 2165.83 2165.24 2164.61 2163.36 2163.14 2162.72 2162.36 2162.73 2162.69 2162.69
 2162.52 2162.52 2162.44 2161.96 2161.89 2161.54 2161.52 2161.09    2161 2161.02
 2161.02 2161.14 2161.32 2161.21 2161.35 2161.76 2161.89    2162 2161.93 2161.97
 2161.79 2162.83 2165.28 2165.31  2165.5  2166.3 2167.65 2170.12 2171.72 2176.65
  2180.3 2180.35 2180.46 2186.33 2189.11 2192.85 2194.48 2199.36 2199.67 2203.28
    2136    2136    2136    2136    2136    2136    2136    2136    2136    2136
    2136    2136    2136    2136    2136    2136    2136    2136    2136    2162
    2162    2136    2136    2136    2136    2136    2136    2136    2136    2136
    2136    2136    2136    2136    2136    2136    2136    2136    2136    2136
    2136    2136    2136    2136    2136    2136    2136    2136    2136    2136
    2136    2136    2136    2136    2136    2136    2136    2136    2136    2136
    4849  4879.8  4880.1  4895.6  4897.3  4908.9  4920.6  4939.9  4952.4  4958.4
  4964.6  4969.9  4974.2  4980.7    4984  4991.5  4992.4  4992.5    4995    4995
    5005    5005  5010.1  5013.6  5014.5  5022.4  5023.1  5030.1  5040.5  5041.6
  5042.4  5052.7  5059.2  5071.5  5076.6  5105.9  5109.8  5133.8  5136.7  5140.1
  5152.7  5185.7    5208  5208.6  5210.3  5218.6  5230.3  5246.7  5258.8    5276
  5290.1  5290.3  5290.6    5308  5316.7  5326.9  5331.7  5346.8  5347.6  5358.7
  2217.9 2210.13 2209.99  2201.6 2200.73 2195.83 2191.03  2181.1 2172.96 2169.33
 2165.83 2165.24 2164.61 2163.36 2163.14 2162.72 2162.36 2162.73 2162.69 2162.69
 2162.52 2162.52 2162.44 2161.96 2161.89 2161.54 2161.52 2161.09    2161 2161.02
 2161.02 2161.14 2161.32 2161.21 2161.35 2161.76 2161.89    2162 2161.93 2161.97
 2161.79 2162.83 2165.28 2165.31  2165.5  2166.3 2167.65 2170.12 2171.72 2176.65
  2180.3 2180.35 2180.46 2186.33 2189.11 2192.85 2194.48 2199.36 2199.67 2203.28
    2136    2136    2136    2136    2136    2136    2136    2136    2136    2136
    2136    2136    2136    2136    2136    2136    2136    2136    2136    2162
    2162    2136    2136    2136    2136    2136    2136    2136    2136    2136
    2136    2136    2136    2136    2136    2136    2136    2136    2136    2136
    2136    2136    2136    2136    2136    2136    2136    2136    2136    2136
    2136    2136    2136    2136    2136    2136    2136    2136    2136    2136
Abutment Skew #Up #Dn= , 2 , 2
    4995    4996
    2162    2156
    4995    4996
    2162 2155.75
Abutment Skew #Up #Dn= , 2 , 2
    5004    5005
    2156    2162
    5004    5005
 2155.75    2162
BR Coef= 1 , 1 , 0 ,1.25, 0 ,,,0.8,0,2,0,
WSPro=,,,, 1 ,,,, 0 ,,,, 0 ,,,,-1 ,-1 ,-1 , 0 , 0 , 0 , 0 , 0
BC Design=,, 0 ,, 0 ,,,,,,
BC HTab HWMax=2214.27

Type RM Length L Ch R = 1 ,1166    ,335,335,335
BEGIN DESCRIPTION:
XS 7
END DESCRIPTION:
XS GIS Cut Line= 4
       750028.78       625531.86       749929.55        625518.7
       749838.42        625534.9       749537.88       625619.13
#Sta/Elev= 30
    4851 2214.94  4862.3 2210.59  4870.5 2208.62  4891.4 2198.22  4907.9 2192.11
  4932.5 2179.17  4949.1 2170.89  4958.7 2168.54  4969.1 2167.07  4974.4 2166.03
    4986 2157.88  4988.1 2156.68    4995 2154.38    5005 2154.38  5007.5    2158
  5009.9 2159.47  5013.1 2160.57  5024.8 2160.39  5048.9  2159.8  5159.9 2160.49
  5187.2 2161.72  5221.9 2165.41  5224.6 2164.74    5231 2167.03  5264.1  2172.2
  5281.7 2176.06  5292.7 2179.19  5306.6 2184.34  5340.6  2194.5  5355.8 2200.35
#Mann= 7 ,-1 , 0
    4851     .09       0  4949.1     .07       0  4969.1     .09       0
    4986     .05       0  5007.5     .09       0  5024.8     .07       0
    5231     .09       0
#XS Ineff= 2 , 0
       0    4971 2165.08    5077       0 2166.56
Permanent Ineff=
       F       F
#Block Obstruct= 1 ,-1
    5077    5135    2170
Bank Sta=4986,5007.5
Exp/Cntr=0.5,0.3

Type RM Length L Ch R = 1 ,831     ,301,301,301
BEGIN DESCRIPTION:
XS 6
END DESCRIPTION:
XS GIS Cut Line= 6
       750058.99       625181.81       749920.03       625196.11
       749752.46       625224.72       749678.89       625267.64
       749552.13       625340.59       749460.04       625452.76
#Sta/Elev= 30
  4655.2 2194.39  4675.2 2187.93  4683.3 2184.79  4693.3  2183.2  4703.6 2182.51
  4820.6 2159.14  4836.8 2157.22  4866.4 2154.65  4935.4 2151.04  4953.9 2148.84
  4974.1  2147.1  4985.6 2145.56  4990.5 2145.38  4994.1 2143.69  4996.3  2141.9
  5004.4  2141.9  5007.4 2143.65  5029.3  2145.5  5090.2 2146.04  5145.7 2147.69
  5180.6 2150.05  5204.6 2152.55  5230.6 2156.49  5256.7 2158.73  5278.7 2163.39
  5293.8 2168.07    5307 2171.23  5322.9 2176.78  5331.4 2179.07  5341.5 2183.06
#Mann= 5 ,-1 , 0
  4655.2     .07       0  4974.1     .09       0  4994.1     .05       0
  5007.4     .09       0  5029.3     .07       0
Bank Sta=4994.1,5007.4
Exp/Cntr=0.3,0.1

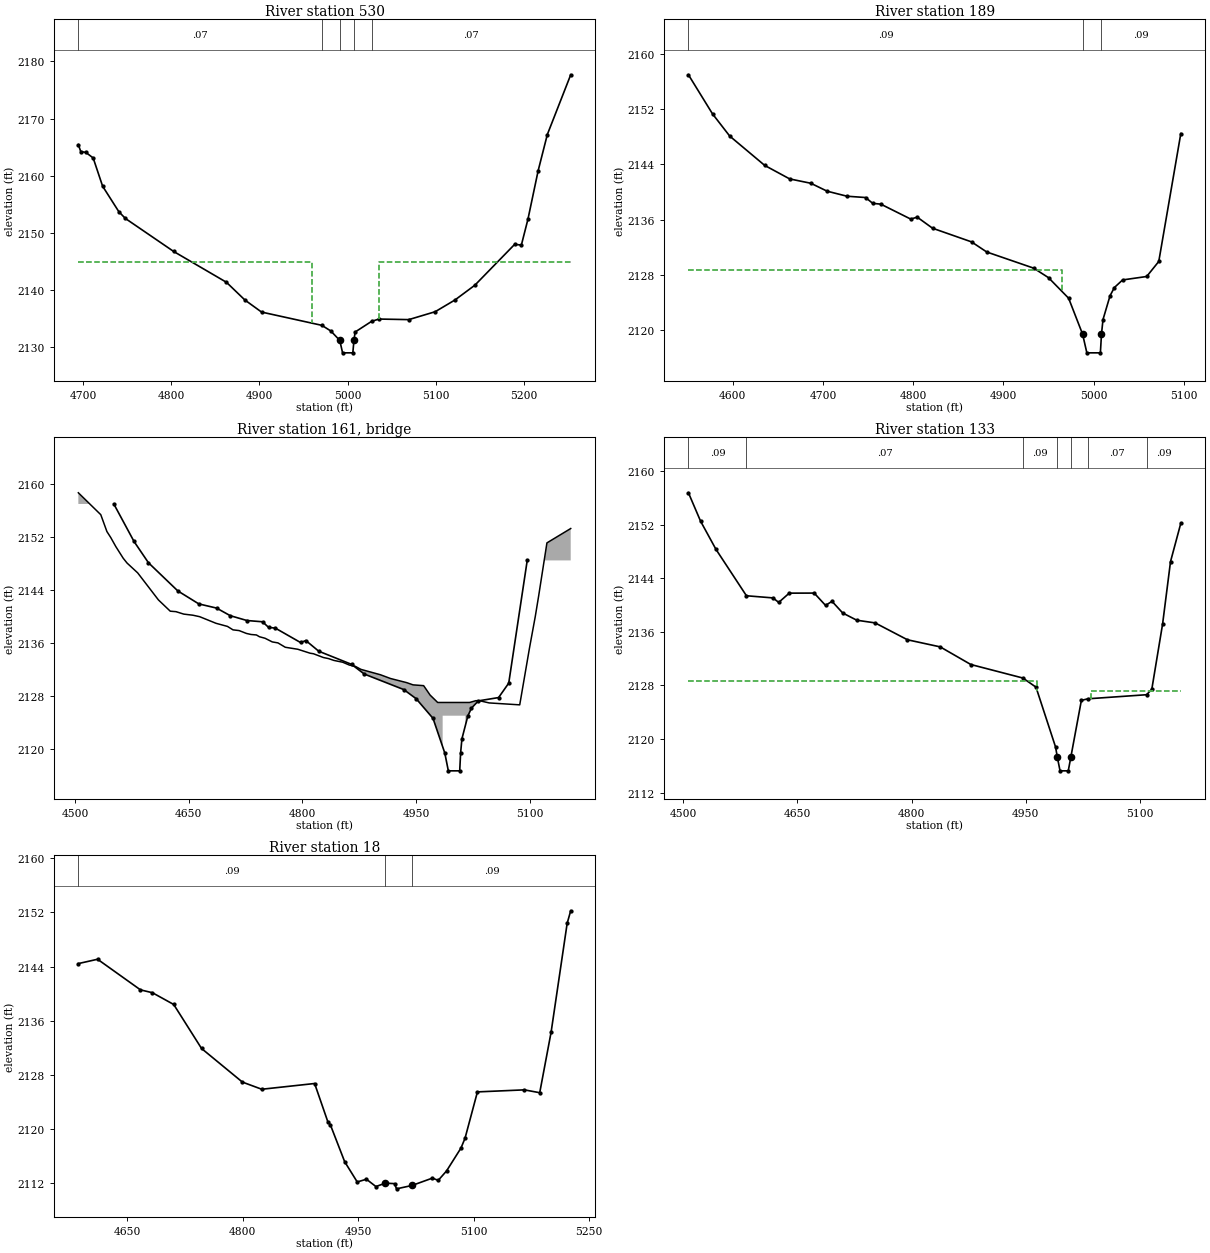
Type RM Length L Ch R = 1 ,530     ,341,341,341
BEGIN DESCRIPTION:
XS 5
END DESCRIPTION:
XS GIS Cut Line= 6
       749844.42       624979.49       749664.58       624977.45
        749562.4       624997.89       749486.79       625051.02
       749403.01       625124.59       749335.57       625142.98
#Sta/Elev= 30
  4694.8 2165.45  4697.5 2164.25  4703.3 2164.09  4711.6 2163.12  4722.3 2158.18
  4740.7 2153.72  4748.1 2152.54  4802.8 2146.77  4862.6 2141.38  4883.5 2138.28
  4902.4 2136.17  4970.7 2133.85  4980.9 2132.86    4991 2131.22  4994.2 2129.04
  5005.8 2129.04  5007.1 2131.23  5008.4 2132.68    5027 2134.54  5035.4 2134.95
  5069.2 2134.85  5099.1 2136.23  5121.6 2138.29  5144.1 2140.87  5189.1    2148
  5196.8  2147.9  5204.2 2152.39  5215.8 2160.89  5226.2 2167.22  5252.7 2177.67
#Mann= 5 ,-1 , 0
  4694.8     .07       0  4970.7     .09       0    4991     .05       0
  5007.1     .09       0    5027     .07       0
#XS Ineff= 2 , 0
       0    4960    2145    5035       0    2145
Permanent Ineff=
       F       F
Bank Sta=4991,5007.1
Exp/Cntr=0.5,0.3

Type RM Length L Ch R = 1 ,189     ,56,56,56
BEGIN DESCRIPTION:
XS 4
END DESCRIPTION:
XS GIS Cut Line= 5
       749776.46       624823.47       749680.94       624741.81
       749445.13       624735.22       749323.39       624738.52
       749283.78        624786.6
#Sta/Elev= 30
    4551 2156.99  4577.7 2151.32  4596.7 2148.11  4635.5 2143.85  4663.2 2141.89
  4686.6 2141.26  4704.7 2140.11  4726.7 2139.38  4747.3 2139.19  4755.2 2138.35
  4764.2 2138.23  4797.4 2136.06  4804.5 2136.35  4821.5 2134.74  4864.7 2132.76
  4881.6 2131.29  4933.6 2128.95    4950 2127.57  4972.3 2124.59  4987.8 2119.37
  4992.5 2116.67  5007.5 2116.67  5008.7 2119.37  5010.4  2121.5  5018.2 2124.95
    5023 2126.14  5032.1 2127.24  5058.8 2127.74  5072.2 2129.92  5096.6 2148.46
#Mann= 3 ,-1 , 0
    4551     .09       0  4987.8     .05       0  5008.7     .09       0
#XS Ineff= 2 , 0
       0    4965 2128.69    5035       0 2127.22
Permanent Ineff=
       F       F
Bank Sta=4987.8,5008.7
Exp/Cntr=0.5,0.3

Type RM Length L Ch R = 3 ,161     ,,,
BEGIN DESCRIPTION:
XS 3 TOR
Structure ID: XS 3
Approximate Survey Structure
END DESCRIPTION:
Bridge Culvert--1,0,-1,-1, 0
Deck Dist Width WeirC Skew NumUp NumDn MinLoCord MaxHiCord MaxSubmerge Is_Ogee
20,16,3,0, 57, 57, , , , 0, 1,1,,
  4504.2  4533.8  4541.9    4547  4553.6  4563.4  4568.5  4582.5  4609.9  4625.5
    4633  4643.3  4655.5  4664.3  4685.9    4701  4708.3  4716.4    4726  4732.1
  4739.2  4743.2  4750.6  4760.1  4767.6  4777.3  4793.8  4810.1  4814.5  4827.6
  4834.3  4841.5  4853.1  4861.9  4869.5  4877.1  4902.8  4916.2  4937.4  4945.9
  4959.9  4968.4  4978.4    4985    4985    5015    5015  5020.6  5028.8  5035.4
  5046.4  5086.7  5099.6  5107.2  5111.7  5122.6    5154
 2158.68 2155.37 2152.82 2151.91 2150.56 2148.79 2148.06 2146.58 2142.49 2140.79
 2140.72 2140.35 2140.18 2139.96 2138.96 2138.49 2137.97 2137.86 2137.43 2137.27
  2137.2 2136.93  2136.7 2136.15    2136 2135.34 2135.04 2134.44 2134.36 2133.79
 2133.63 2133.35 2133.08 2132.65 2132.47    2132 2131.19 2130.62    2130 2129.66
 2129.54 2128.12    2127    2127    2127    2127    2127    2127 2127.27 2127.22
 2126.93 2126.64 2135.23 2139.97  2143.1 2151.11 2153.28
  2095.5  2095.5  2095.5  2095.5  2095.5  2095.5  2095.5  2095.5  2095.5  2095.5
  2095.5  2095.5  2095.5  2095.5  2095.5  2095.5  2095.5  2095.5  2095.5  2095.5
  2095.5  2095.5  2095.5  2095.5  2095.5  2095.5  2095.5  2095.5  2095.5  2095.5
  2095.5  2095.5  2095.5  2095.5  2095.5  2095.5  2095.5  2095.5  2095.5  2095.5
  2095.5  2095.5  2095.5  2095.5    2125    2125  2095.5  2095.5  2095.5  2095.5
  2095.5  2095.5  2095.5  2095.5  2095.5  2095.5  2095.5
  4504.2  4533.8  4541.9    4547  4553.6  4563.4  4568.5  4582.5  4609.9  4625.5
    4633  4643.3  4655.5  4664.3  4685.9    4701  4708.3  4716.4    4726  4732.1
  4739.2  4743.2  4750.6  4760.1  4767.6  4777.3  4793.8  4810.1  4814.5  4827.6
  4834.3  4841.5  4853.1  4861.9  4869.5  4877.1  4902.8  4916.2  4937.4  4945.9
  4959.9  4968.4  4978.4    4985    4985    5015    5015  5020.6  5028.8  5035.4
  5046.4  5086.7  5099.6  5107.2  5111.7  5122.6    5154
 2158.68 2155.37 2152.82 2151.91 2150.56 2148.79 2148.06 2146.58 2142.49 2140.79
 2140.72 2140.35 2140.18 2139.96 2138.96 2138.49 2137.97 2137.86 2137.43 2137.27
  2137.2 2136.93  2136.7 2136.15    2136 2135.34 2135.04 2134.44 2134.36 2133.79
 2133.63 2133.35 2133.08 2132.65 2132.47    2132 2131.19 2130.62    2130 2129.66
 2129.54 2128.12    2127    2127    2127    2127    2127    2127 2127.27 2127.22
 2126.93 2126.64 2135.23 2139.97  2143.1 2151.11 2153.28
  2095.5  2095.5  2095.5  2095.5  2095.5  2095.5  2095.5  2095.5  2095.5  2095.5
  2095.5  2095.5  2095.5  2095.5  2095.5  2095.5  2095.5  2095.5  2095.5  2095.5
  2095.5  2095.5  2095.5  2095.5  2095.5  2095.5  2095.5  2095.5  2095.5  2095.5
  2095.5  2095.5  2095.5  2095.5  2095.5  2095.5  2095.5  2095.5  2095.5  2095.5
  2095.5  2095.5  2095.5  2095.5    2125    2125  2095.5  2095.5  2095.5  2095.5
  2095.5  2095.5  2095.5  2095.5  2095.5  2095.5  2095.5
Abutment Skew #Up #Dn= , 2 , 2
    4985    4990
    2125  2116.5
    4985    4990
    2125 2116.25
Abutment Skew #Up #Dn= , 2 , 2
    5010    5015
  2116.5    2125
    5010    5015
 2116.25    2125
BR Coef= 1 , 1 , 0 ,1.25, 0 ,,,0.8,0,2,0,
WSPro=,,,, 1 ,,,, 0 ,,,, 0 ,,,,-1 ,-1 ,-1 , 0 , 0 , 0 , 0 , 0
BC Design=,, 0 ,, 0 ,,,,,,
BC HTab HWMax=2156.99

Type RM Length L Ch R = 1 ,133     ,115,115,115
BEGIN DESCRIPTION:
XS 2
END DESCRIPTION:
XS GIS Cut Line= 6
       749794.89        624793.3       749716.04       624686.97
       749577.84       624684.77       749396.87       624682.58
       749299.26       624680.39       749253.62       624766.49
#Sta/Elev= 30
  4506.8 2156.75  4522.8  2152.5    4543  2148.3    4583 2141.38  4617.8 2141.06
  4625.4 2140.39  4639.2 2141.77    4672 2141.78  4686.9 2139.94  4695.4 2140.55
  4709.4 2138.81  4727.9 2137.73    4752 2137.33  4794.5 2134.81  4837.5 2133.75
  4877.7 2131.12  4946.1  2129.1  4963.3 2127.74    4989 2118.81  4991.4 2117.25
  4994.9 2115.25  5005.7 2115.25    5009 2117.25  5022.9 2125.76  5031.3    2126
  5108.5 2126.61  5115.4 2127.41  5129.6 2137.17    5140 2146.48  5153.5 2152.19
#Mann= 7 ,-1 , 0
  4506.8     .09       0    4583     .07       0  4946.1     .09       0
  4991.4     .05       0    5009     .09       0  5031.3     .07       0
  5108.5     .09       0
#XS Ineff= 2 , 0
       0    4965 2128.69    5035       0 2127.22
Permanent Ineff=
       F       F
Bank Sta=4991.4,5009
Exp/Cntr=0.5,0.3

Type RM Length L Ch R = 1 ,18      ,0,0,0
BEGIN DESCRIPTION:
XS 1
END DESCRIPTION:
XS GIS Cut Line= 6
        749746.3       624585.51       749577.04       624550.32
       749386.01       624535.23       749307.24       624602.26
       749273.73       624664.27       749238.54       624759.79
#Sta/Elev= 30
  4586.2 2144.44  4611.2 2145.08    4667 2140.55  4682.5 2140.13  4710.2 2138.39
  4746.4 2131.88  4799.5 2126.91  4824.7 2125.85  4893.4  2126.7  4910.5 2121.07
    4914 2120.56  4932.5 2115.13  4948.8 2112.14  4960.8 2112.54  4973.1 2111.46
  4985.4 2111.96  4997.3 2111.89  4999.9 2111.12  5020.1 2111.62  5046.6 2112.71
  5054.1 2112.37  5064.9 2113.76  5083.7 2117.15    5089 2118.61  5105.1 2125.46
  5166.1 2125.76  5186.1 2125.34  5200.9 2134.29  5221.8 2150.41  5226.4 2152.25
#Mann= 3 , 0 , 0
  4586.2     .09       0  4985.4     .05       0  5020.1     .09       0
Bank Sta=4985.4,5020.1
Exp/Cntr=0.3,0.1

Chan Stop Cuts=-1
Use User Specified Reach Order=0
User Specified Reach Order=Fisher Creek    ,Reach-1